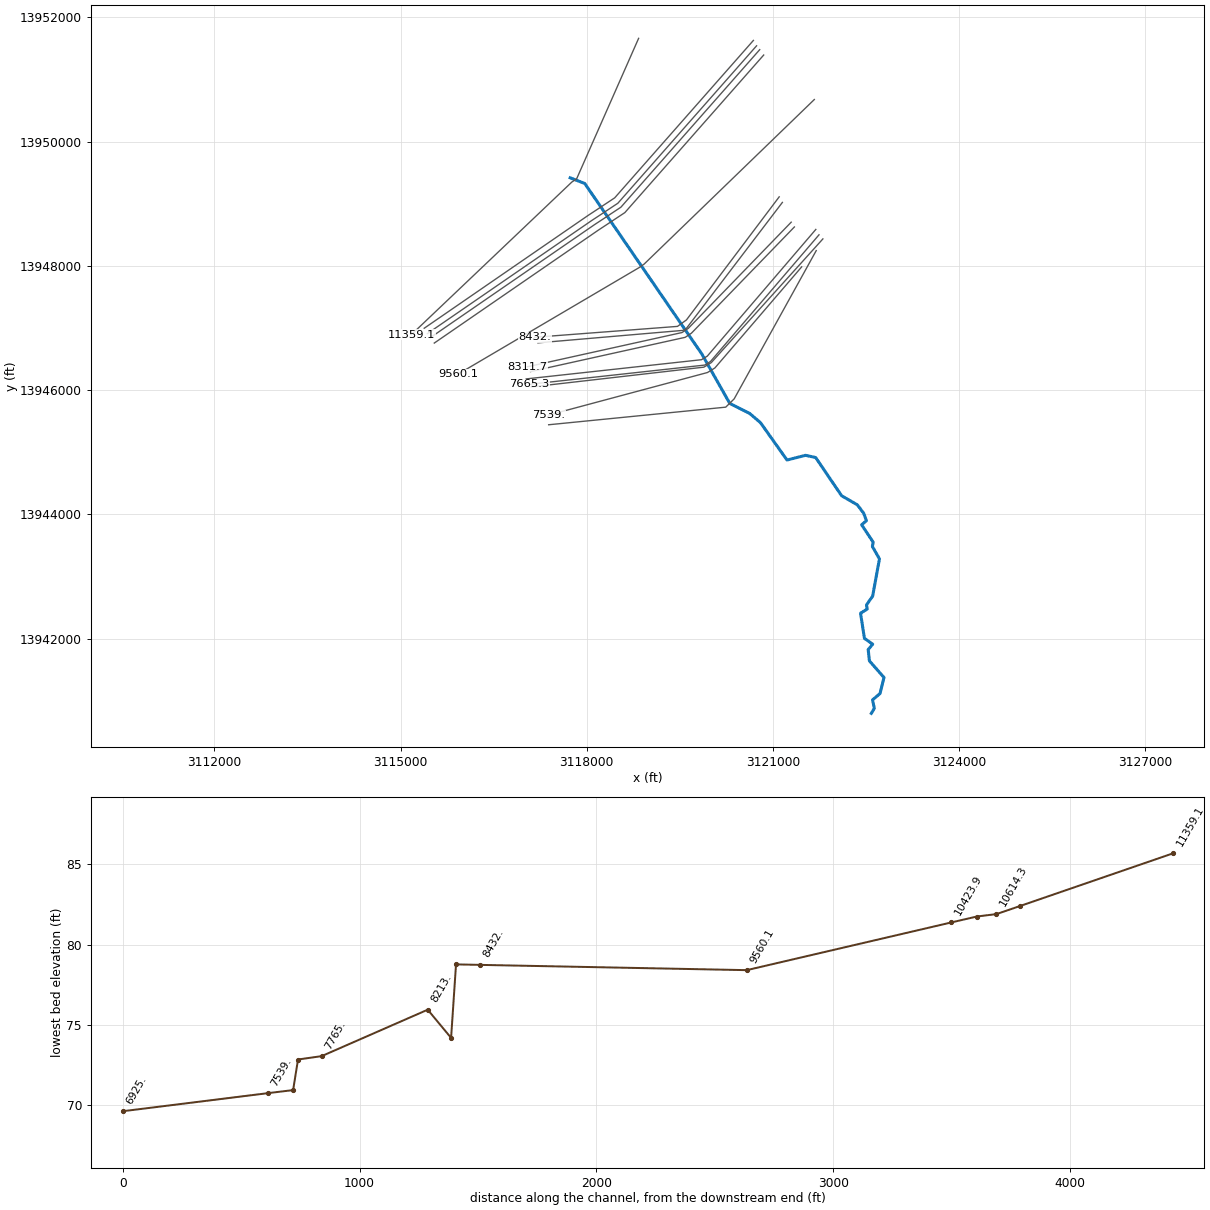
--- K112-00-00.prj (project) ---

Proj Title=K112-00-00
Current Plan=p02
Default Exp/Contr=.3,.1
English Units
Geom File=g01
Flow File=f02
Flow File=f01
Flow File=f04
Plan File=p01
Plan File=p04
Plan File=p02
Y Axis Title=Elevation
X Axis Title(PF)=Main Channel Distance
X Axis Title(XS)=Station
BEGIN DESCRIPTION:
Cypress Watershed
Wild Cow Gulch
HCFCD Unit K112-00-00
Flood Hazard Model
10, 2, 1, 0.2%
Filename K112-00-00
Prepared by:  Halff Associates  DATE:  March 26, 2004
Reviewed by:  _________  DATE:  __________________
STATUS (Final)
END DESCRIPTION:
DSS File=dss
DSS Export Rating Curves= 0
DSS Export Rating Curve Sorted= 0
DSS Export Volume Flow Curves= 0
DXF OffsetX= 0
DXF OffsetY= 0
DXF ScaleX= 1
DXF ScaleY= 10

--- K112-00-00.p02 (plan) ---

Plan Title=Floodway
Version=Version 3.0.1  Mar 2001
Short Identifier=Floodway0607
Geom File=g01
Flow File=f02
Subcritical Flow
K Sum by GR= 0
Std Step Tol= 0.01
Critical Tol= 0.01
Num of Std Step Trials= 20
Max Error Tol= 0.3
Flow Tol Ratio= 0.001
Split Flow NTrial= 30
Split Flow Tol= 0.02
Split Flow Ratio= 0.02
Log Output Level= 0
Friction Slope Method= 1
Unsteady Friction Slope Method= 2
Parabolic Critical Depth
Global Vel Dist= 0 , 0 , 0
Global Log Level= 0
CheckData=True
Encroach Param=-1 ,0,0, 3
Encroach River=K112-00-00
Encroach Reach=Reach - 1
Encroach Node=11359.1
       1  4931.9  5030.1       1  4931.9  5030.1
Encroach Node=10713.
       1  4903.3  5094.1       1  4903.3  5094.1
Encroach Node=10614.3
       1  4874.3  5116.6       1  4874.3  5116.6
Encroach Node=10573.0
       1  4874.3  5116.6       1  4874.3  5116.6
Encroach Node=10531.8
       1  4904.3  5086.6       1  4904.3  5086.6
Encroach Node=10423.9
       1  4912.9  5086.3       1  4912.9  5086.3
Encroach Node=9560.1
       1  4963.6  5045.7       1  4963.6  5045.7
Encroach Node=8432.
       1    4865  5053.7       1    4865  5053.7
Encroach Node=8332.5
       1    4865  5046.2       1    4865  5046.2
Encroach Node=8322.0
       1    4865  5044.4       1    4865  5044.4
Encroach Node=8311.7
       1    4865  5044.4       1    4865  5044.4
Encroach Node=8213.
       1    4920    5072       1    4920    5072
Encroach Node=7765.
       1  4932.3  5062.4       1  4932.3  5062.4
Encroach Node=7665.3
       1 4923.72 5075.36       1 4923.72 5075.36
Encroach Node=7655.0
       1 4923.72 5075.36       1 4923.72 5075.36
Encroach Node=7644.7
       1 4923.72 5075.36       1 4923.72 5075.36
Encroach Node=7539.
       1  4941.9  5055.5       1  4941.9  5055.5
Encroach Node=6925.
       1  4948.2  5098.6       1  4948.2  5098.6
Encroach Node=6825.8
       1  4949.9  5054.5       1  4949.9  5054.5
Encroach Node=6796.5
       1  4949.9  5054.5       1  4949.9  5054.5
Encroach Node=6767.2
       1  4949.9  5054.5       1  4949.9  5054.5
Encroach Node=6469.1
       1  4958.9  5039.6       1  4958.9  5039.6
Encroach Node=6454.1
       1  4958.9  5039.6       1  4958.9  5039.6
Encroach Node=6439.1
       1  4958.2  5038.7       1  4958.2  5038.7
Encroach Node=6328.
       1    4962  5069.3       1    4962  5069.3
Encroach Node=5510.9
       1  4944.8  5051.4       1  4944.8  5051.4
Encroach Node=4417.
       1  4936.2  5056.2       1  4936.2  5056.2
Encroach Node=4313.6
       1    4975  5032.6       1    4975  5032.6
Encroach Node=4283.9
       1    4975  5032.6       1    4975  5032.6
Encroach Node=4232.5
       1    4975  5032.6       1    4975  5032.6
Encroach Node=4137.
       1  4967.1  5057.1       1  4967.1  5057.1
Encroach Node=3534.0
       1 4944.82  5048.3       1 4944.82  5048.3
Encroach Node=3145.0
       1 4907.37  5108.6       1 4907.37  5108.6
Encroach Node=1643.1
       1 4971.79 5031.56       1 4971.79 5031.56
Encroach Node=505.0
       1 4970.32 5031.37       1 4970.32 5031.37
Encroach Reach=K112-00-00_0005
Encroach Node=11359.1
       1  4931.9  5030.1       0       0       0
Encroach Node=10713.
       1  4903.3  5094.1       0       0       0
Encroach Node=10614.3
       1  4874.3  5116.6       0       0       0
Encroach Node=10573.0
       1  4874.3  5116.6       0       0       0
Encroach Node=10531.8
       1  4904.3  5086.6       0       0       0
Encroach Node=10423.9
       1  4912.9  5086.3       0       0       0
Encroach Node=9560.1
       1  4963.6  5045.7       0       0       0
Encroach Node=8432.
       1    4865  5053.7       0       0       0
Encroach Node=8332.5
       1    4865  5046.2       0       0       0
Encroach Node=8322.0
       1    4865  5044.4       0       0       0
Encroach Node=8311.7
       1    4865  5044.4       0       0       0
Encroach Node=8213.
       1    4920    5072       0       0       0
Encroach Node=7765.
       1  4932.3  5062.4       0       0       0
Encroach Node=7665.3
       1 4923.72 5075.36       0       0       0
Encroach Node=7655.0
       1 4923.72 5075.36       0       0       0
Encroach Node=7644.7
       1 4923.72 5075.36       0       0       0
Encroach Node=7539.
       1  4941.9  5055.5       0       0       0
Encroach Node=6925.
       1  4948.2  5098.6       0       0       0
Encroach Node=6825.8
       1  4949.9  5054.5       0       0       0
Encroach Node=6796.5
       1  4949.9  5054.5       0       0       0
Encroach Node=6767.2
       1  4949.9  5054.5       0       0       0
Encroach Node=6469.1
       1  4958.9  5039.6       0       0       0
Encroach Node=6454.1
       1  4958.9  5039.6       0       0       0
Encroach Node=6439.1
       1  4958.2  5038.7       0       0       0
Encroach Node=6328.
       1    4962  5069.3       0       0       0
Encroach Node=5510.9
       1  4944.8  5051.4       0       0       0
Encroach Node=4417.
       1  4936.2  5056.2       0       0       0
Encroach Node=4313.6
       1    4975  5032.6       0       0       0
Encroach Node=4283.9
       1    4975  5032.6       0       0       0
Encroach Node=4232.5
       1    4975  5032.6       0       0       0
Encroach Node=4137.
       1  4967.1  5057.1       0       0       0
Encroach Node=3534.0
       1 4944.82  5048.3       0       0       0
Encroach Node=3145.0
       1 4907.37  5108.6       0       0       0
Encroach Node=1643.1
       1 4971.79 5031.56       0       0       0
Encroach Node=505.0
       1 4970.32 5031.37       0       0       0
Computation Interval=1HOUR
Output Interval=1HOUR
Run HTab= 0
Run UNet= 0
Run PostProcess= 0
UNET Theta= 1
UNET ZTol= 0.02
UNET ZSATol= 0.1
UNET MxIter= 20
UNET MaxInSteps= 20
UNET DtIC= 0
UNET DtMin= 0
UNET MaxCRTS= 20
UNET WFStab= 2
UNET SFStab= 1
UNET WFX= 1
UNET SFX= 1
UNET Convert EG Bridges=-1
UNET Use Existing IB Tables=-1
Instantaneous Interval=1HOUR
Write IC File= 0
Write Velocity= 0
Write Detailed= 0

--- K112-00-00.p01 (plan) ---

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Plan Title=FEMA Effective June 2007
Short Identifier=FEMAeff0607
Geom File=g01
Flow File=f01
Encroach Param=-1 ,0,0, 2
IC Time=0

--- K112-00-00.p04 (plan) ---

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Plan Title=Storage Routing
Short Identifier=Store_Rout
Geom File=g01
Flow File=f04
Encroach Param=-1 ,0,0, 0

--- K112-00-00.f02 (steady flow) ---

Flow Title=Floodway
Version=Version 3.0.1  Mar 2001
Number of Profiles= 2
Profile Names=1PCT_100yr, 1PCTFloodway_100yrFW
River Rch & RM=K112-00-00,K112-00-00_0005,11359.1
    1660    1660
River Rch & RM=K112-00-00,K112-00-00_0005,10531.8
    1860    1860
River Rch & RM=K112-00-00,K112-00-00_0005,9560.1
    2160    2160
River Rch & RM=K112-00-00,K112-00-00_0005,8332.5
    2340    2340
River Rch & RM=K112-00-00,K112-00-00_0005,7665.3
    2590    2590
River Rch & RM=K112-00-00,K112-00-00_0005,6825.8
    2700    2700
River Rch & RM=K112-00-00,K112-00-00_0005,6469.1
    2790    2790
River Rch & RM=K112-00-00,K112-00-00_0005,5510.9
    2900    2900
River Rch & RM=K112-00-00,K112-00-00_0005,4232.5
    3500    3500
River Rch & RM=K112-00-00,K112-00-00_0005,3534.0
    3676    3676
Boundary for River Rch & Prof#=K112-00-00,K112-00-00_0005, 1
Up Type= 0
Dn Type= 3
Dn Slope=.0048384
Boundary for River Rch & Prof#=K112-00-00,K112-00-00_0005, 2
Up Type= 0
Dn Type= 1
Dn Known WS=61.27
DSS Import GetInterval= 0
DSS Import GetPeak= 0
DSS Import FillOption= 0

--- K112-00-00.f01 (steady flow) ---

Flow Title=FEMA Effective June 2007
Version=Version 3.0.1  Mar 2001
Number of Profiles= 4
Profile Names=10PCT_10yr, 2PCT_50yr, 1PCT_100yr, 0.2PCT_500yr
River Rch & RM=K112-00-00,K112-00-00_0005,11359.1
     890    1430    1660    2110
River Rch & RM=K112-00-00,K112-00-00_0005,10531.8
    1010    1600    1860    2380
River Rch & RM=K112-00-00,K112-00-00_0005,9560.1
    1180    1850    2160    2780
River Rch & RM=K112-00-00,K112-00-00_0005,8332.5
    1290    2000    2340    3020
River Rch & RM=K112-00-00,K112-00-00_0005,7665.3
    1440    2210    2590    3350
River Rch & RM=K112-00-00,K112-00-00_0005,6825.8
    1500    2300    2700    3500
River Rch & RM=K112-00-00,K112-00-00_0005,6469.1
    1580    2390    2790    3710
River Rch & RM=K112-00-00,K112-00-00_0005,5510.9
    1700    2500    2900    4000
River Rch & RM=K112-00-00,K112-00-00_0005,4232.5
    2000    3000    3500    4900
River Rch & RM=K112-00-00,K112-00-00_0005,3534.0
    2119    3184    3676    5160
Boundary for River Rch & Prof#=K112-00-00,K112-00-00_0005, 1
Up Type= 0
Dn Type= 3
Dn Slope=.0048384
Boundary for River Rch & Prof#=K112-00-00,K112-00-00_0005, 2
Up Type= 0
Dn Type= 3
Dn Slope=.0048384
Boundary for River Rch & Prof#=K112-00-00,K112-00-00_0005, 3
Up Type= 0
Dn Type= 3
Dn Slope=.0048384
Boundary for River Rch & Prof#=K112-00-00,K112-00-00_0005, 4
Up Type= 0
Dn Type= 3
Dn Slope=.0048384
DSS Import GetInterval= 0
DSS Import GetPeak= 0
DSS Import FillOption= 0

--- K112-00-00.f04 (steady flow) ---

Flow Title=Storage Routing
Version=Version 3.0.1  Mar 2001
Number of Profiles= 7
Profile Names=0.25*10% flood, 0.50*10%flood, 10% flood, 2% flood, 1% flood, 0.2%flood, 1.25*0.2% flood
River Rch & RM=K112-00-00,K112-00-00_0005,11359.1
      40      80     160     280     360     430     540
River Rch & RM=K112-00-00,K112-00-00_0005,10614.25
     143     285     570     940    1080    1330    1660
River Rch & RM=K112-00-00,K112-00-00_0005,8322
     193     385     770    1160    1330    1650    2060
River Rch & RM=K112-00-00,K112-00-00_0005,7655
     250     500    1000    1460    1630    2030    2540
River Rch & RM=K112-00-00,K112-00-00_0005,6796.5
     315     630    1260    1770    1960    2460    3075
River Rch & RM=K112-00-00,K112-00-00_0005,5510.9
     365     730    1460    2020    2270    2860    3575
River Rch & RM=K112-00-00,K112-00-00_0005,4313.6
     485     970    1940    2640    3000    3810    4760
Boundary for River Rch & Prof#=K112-00-00,K112-00-00_0005, 1
Up Type= 0
Dn Type= 3
Dn Slope=.0048384
Boundary for River Rch & Prof#=K112-00-00,K112-00-00_0005, 2
Up Type= 0
Dn Type= 3
Dn Slope=.0048384
Boundary for River Rch & Prof#=K112-00-00,K112-00-00_0005, 3
Up Type= 0
Dn Type= 3
Dn Slope=.0048384
Boundary for River Rch & Prof#=K112-00-00,K112-00-00_0005, 4
Up Type= 0
Dn Type= 3
Dn Slope=.0048384
Boundary for River Rch & Prof#=K112-00-00,K112-00-00_0005, 5
Up Type= 0
Dn Type= 3
Dn Slope=.0048384
Boundary for River Rch & Prof#=K112-00-00,K112-00-00_0005, 6
Up Type= 0
Dn Type= 3
Dn Slope=.0048384
Boundary for River Rch & Prof#=K112-00-00,K112-00-00_0005, 7
Up Type= 0
Dn Type= 3
Dn Slope=.0048384
DSS Import GetInterval= 0
DSS Import GetPeak= 0
DSS Import FillOption= 0

--- K112-00-00.g01 (geometry) ---

Geom Title=K112-00-00 June 2007
Version=Version 3.0.1  Mar 2001

River Reach=K112-00-00      ,K112-00-00_0005
Reach XY= 30
      3117732.53     13949415.46      3117967.13     13949324.62
      3119853.42      13946580.7      3120303.07     13945785.56
      3120625.99     13945622.37      3120798.75       13945475.
      3121225.81      13944874.1      3121523.56     13944949.62
      3121687.62     13944914.03      3122105.75       13944299.
      3122359.49     13944152.75      3122461.06     13944017.33
      3122505.33     13943897.54      3122428.07     13943831.57
       3122614.7     13943550.32      3122600.81     13943483.48
       3122715.4     13943282.96      3122605.15     13942683.13
       3122506.2     13942541.64      3122517.48     13942475.66
      3122410.71     13942408.82      3122473.21     13942004.31
      3122606.02     13941909.69      3122533.97     13941823.75
      3122553.07     13941642.33      3122788.31      13941374.1
      3122724.08     13941115.42      3122603.42     13941013.86
      3122632.93     13940877.57      3122584.32      13940796.8

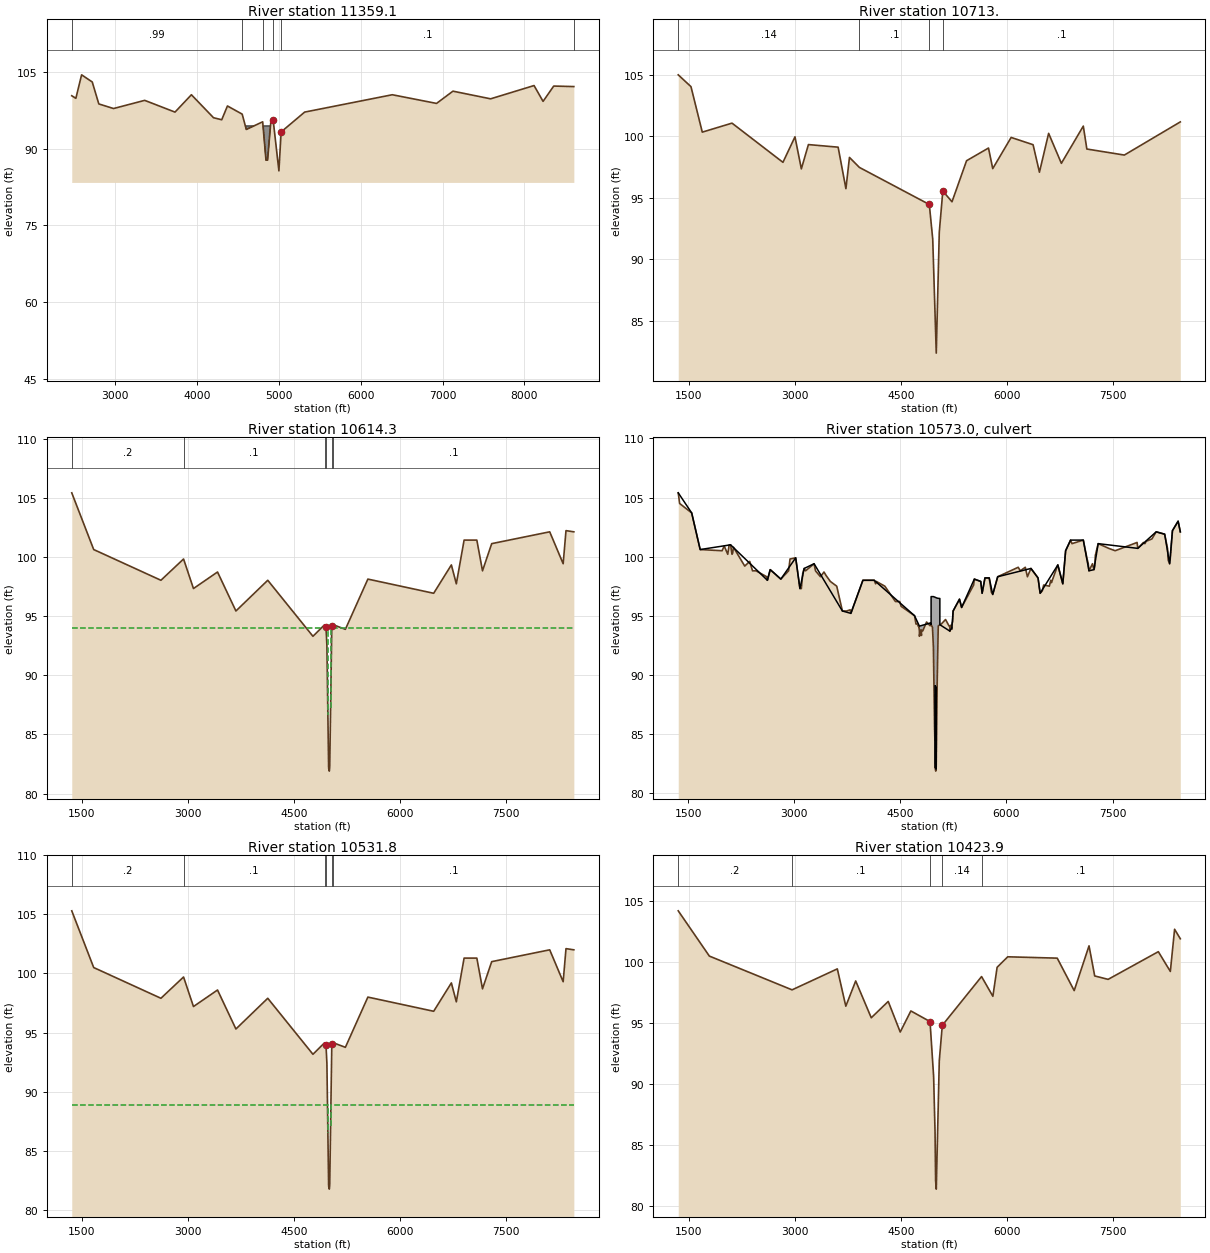
Type RM Length L Ch R = 1 ,11359.1 ,693,646.1,595
BEGIN DESCRIPTION:
Cross Section K112-00-00-X07; Detention pond on left VRR
END DESCRIPTION:
XS GIS Cut Line= 4
      3118835.23     13951660.29       3117835.8     13949397.33
      3117761.66     13949349.54      3115176.49     13946893.86
#Sta/Elev= 30
  2474.7   100.4  2524.7    99.9  2594.7   104.5  2724.7   103.1  2804.7    98.8
  2984.7    97.9  3364.7    99.5  3734.7    97.2  3934.7   100.6  4204.7    96.1
  4304.7    95.7  4374.7    98.4  4554.7    96.8  4604.7    93.8  4804.7    95.3
  4844.7    87.8  4864.7    87.8  4904.7    95.4  4931.9   95.74  5002.7   85.69
  5030.1   93.32  5316.7    97.2  6386.7   100.6  6926.7    98.9  7126.7   101.3
  7586.7    99.8  8116.7   102.4  8226.7    99.3  8356.7   102.3  8602.3   102.2
#Mann= 6 ,-1 , 0
  2474.7     .99       0  4554.7      .1       0  4804.7    .026       0
  4931.9     .04       0  5030.1      .1       0  8602.3      .2       0
#Block Obstruct= 2 ,-1
    4500  4931.9    94.5    9000    9001      50
Bank Sta=4931.9,5030.1
XS Rating Curve= 0
Exp/Cntr=.3,.1

Type RM Length L Ch R = 1 ,10713.  ,99.4,98.7,98.3
BEGIN DESCRIPTION:
K112-00-00-S6_HICKORY GATE DR - US - XS 4
LIDAR overbanks - interpolated channel
END DESCRIPTION:
XS GIS Cut Line= 6
      3120684.48     13951626.87      3118449.54     13949093.09
      3118300.84     13948994.78      3118190.58     13948921.28
      3118026.92     13948814.01      3115380.99     13946994.71
#Sta/Elev= 30
  1354.7  104.98  1534.7  104.02  1694.7  100.33  2114.7  101.06  2834.7   97.88
  3004.7   99.95  3094.7   97.35  3194.7   99.32  3614.7   99.11  3724.7   95.74
  3774.7   98.28  3914.7   97.47  4903.3   94.46  4951.6   91.66 5001.57    82.4
  5044.1    92.2  5094.1   95.55  5224.1   94.68  5429.8   98.01  5739.8   99.04
  5799.8   97.37  6059.8    99.9  6369.8   99.31  6459.8   97.08  6589.8  100.23
  6769.8    97.8  7079.8  100.82  7129.8   98.96  7659.8   98.47  8450.8  101.16
#Mann= 4 ,-1 , 0
  1354.7     .14       0  3914.7      .1       0  4903.3     .04       0
  5094.1      .1       0
Bank Sta=4903.3,5094.1
XS Rating Curve= 0
Exp/Cntr=.5,.3

Type RM Length L Ch R = 1 ,10614.3 ,82.5,82.5,82.5
BEGIN DESCRIPTION:
Upstream Section of Bridge/Culvert/Weir
END DESCRIPTION:
XS GIS Cut Line= 6
      3120735.76     13951540.33      3118500.82     13949006.55
      3118352.12     13948908.24      3118241.87     13948834.74
       3118078.2     13948727.47      3115432.27     13946908.17
#Sta/Elev= 30
  1361.4  105.45  1671.4  100.65  2621.4   98.05  2941.4   99.85  3081.4   97.35
  3421.4   98.75  3681.4   95.45  4131.4   98.05  4770.2   93.31 4935.19   94.29
  4954.3   94.08  4967.4   92.54  4991.8   82.16  5001.4    81.9  5007.4   82.28
  5036.6   94.19 5059.21   94.28  5228.6    93.9  5546.5   98.15  6476.5   96.95
  6726.5   99.35  6796.5   97.75  6906.5  101.45  7086.5  101.45  7166.5   98.85
  7296.5  101.15  8116.5  102.15  8306.5   99.45  8346.5  102.25  8457.5  102.15
#Mann= 6 ,-1 , 0
  1361.4      .2       0  2941.4      .1       0 4935.19    .045       0
  4954.3     .04       0  5036.6    .045       0 5059.21      .1       0
#XS Ineff= 2 , 0
       0  4981.2   94.05  5019.6       0   94.05
Permanent Ineff=
       F       F
Bank Sta=4954.3,5036.6
XS Rating Curve= 0
Exp/Cntr=.5,.3

Type RM Length L Ch R = 2 ,10573.0 ,,,
BEGIN DESCRIPTION:
HICKORY GATE DRIVE
Structure ID: K112-00-00-S6
END DESCRIPTION:
Bridge Culvert--1,0,-1,-1, 0
Deck Dist Width WeirC Skew NumUp NumDn MinLoCord MaxHiCord MaxSubmerge Is_Ogee
10,62.5,3,0, 60, 60, , , .95, 0, ,,,
  1361.4  1551.4  1671.4  2101.4  2621.4  2661.4  2811.4  3021.4  3081.4  3141.4
  3281.4  3681.4  3801.4  3971.4  4131.4  4701.4  4770.2  4922.9 4935.19  4935.3
  4954.3  4967.4  4989.4  4991.8  5001.4  5007.4    5022  5036.6  5059.1 5059.21
  5199.7  5228.6  5246.5  5336.5  5366.5  5546.5  5636.5  5656.5  5696.5  5756.5
  5806.5  5876.5  6346.5  6446.5  6476.5  6726.5  6796.5  6836.5  6906.5  7086.5
  7166.5  7236.5  7296.5  7856.5  8116.5  8236.5  8306.5  8346.5  8426.5  8457.5
   105.4   103.7   100.6     101      98    98.9    98.1    99.9    97.3      99
    99.4    95.4    95.2      98      98      95   94.12   94.38   94.25   96.62
   96.62   96.62   96.57   96.56   96.54   96.52   96.49   96.47   96.46   94.24
    93.7   93.99    95.4    96.4    95.7    98.1    97.9    96.9    98.2    98.2
    96.8    98.3      99    98.2    96.9    99.3    97.7   100.5   101.4   101.4
    98.8    98.9   101.1   100.7   102.1   101.9    99.4   102.2     103   102.1
   105.4   103.7   100.6     101      98    98.9    98.1    99.9    97.3      99
    99.4    95.4    95.2      98      98      95   93.26   94.37   94.24   94.24
   94.03   92.49   84.35   82.11   81.85   82.23   89.56   94.14   94.23   94.23
   93.68   93.85    95.4    96.4    95.7    98.1    97.9    96.9    98.2    98.2
    96.8    98.3      99    98.2    96.9    99.3    97.7   100.5   101.4   101.4
    98.8    98.9   101.1   100.7   102.1   101.9    99.4   102.2     103   102.1
  1361.4  1551.4  1671.4  2101.4  2621.4  2661.4  2811.4  3021.4  3081.4  3141.4
  3281.4  3681.4  3801.4  3971.4  4131.4  4701.4  4770.2  4922.9 4935.19  4935.3
  4954.3  4967.4  4989.4  4991.8  5001.4  5007.4    5022  5036.6  5059.1 5059.21
  5199.7  5228.6  5246.5  5336.5  5366.5  5546.5  5636.5  5656.5  5696.5  5756.5
  5806.5  5876.5  6346.5  6446.5  6476.5  6726.5  6796.5  6836.5  6906.5  7086.5
  7166.5  7236.5  7296.5  7856.5  8116.5  8236.5  8306.5  8346.5  8426.5  8457.5
   105.4   103.7   100.6     101      98    98.9    98.1    99.9    97.3      99
    99.4    95.4    95.2      98      98      95   94.12   94.38   94.25   96.62
   96.62   96.62   96.57   96.56   96.54   96.52   96.49   96.47   96.46   94.24
    93.7   93.99    95.4    96.4    95.7    98.1    97.9    96.9    98.2    98.2
    96.8    98.3      99    98.2    96.9    99.3    97.7   100.5   101.4   101.4
    98.8    98.9   101.1   100.7   102.1   101.9    99.4   102.2     103   102.1
  105.34  103.64  100.54  100.94   97.94   98.84   98.04   99.84   97.24   98.94
   99.34   95.34   95.14   97.94   97.94   94.94    93.2   94.31   94.18   94.18
   93.97   92.43   84.29   82.05   81.79   82.17    89.5   94.08   94.17   94.17
   93.62   93.79   95.34   96.34   95.64   98.04   97.84   96.84   98.14   98.14
   96.74   98.24   98.94   98.14   96.84   99.24   97.64  100.44  101.34  101.34
   98.74   98.84  101.04  100.64  102.04  101.84   99.34  102.14  102.94  102.04
BR Coef= 1 , 0 , 0 ,1.25, 0 ,,,.8,0,2,0,
WSPro=,,,, 1 ,,,, 0 ,,,, 0 ,,,,-1 ,-1 ,-1 , 0 , 0 , 0 , 0 , 0
Culvert=1,7,,62.5,.015,.2,1,1,2,82.13,4994.7,81.86,4994.7,Culvert #1  , 0 ,10
Culvert Bottom n=.015
Culvert=1,7,,62.5,.015,.2,1,1,2,82,5006.1,81.86,5006.1,Culvert #2  , 0 ,10
Culvert Bottom n=.015
BR U #Sta/Elev= 159
  1361.4   105.4  1381.4   104.5  1551.4   103.7  1671.4   100.6  1981.4   100.5
  2011.4   100.9  2061.4   100.2  2081.4     101  2101.4     101  2121.4   100.2
  2131.4   100.3  2141.4   100.8  2301.4    99.2  2371.4    99.6  2411.4    98.8
  2461.4    98.8  2611.4    98.3  2621.4      98  2661.4    98.9  2811.4    98.1
  2921.4    98.8  2941.4    99.8  3021.4    99.9  3081.4    97.3  3101.4    97.3
  3121.4    98.6  3141.4      99  3161.4    98.8  3281.4    99.4  3301.4    98.8
  3371.4    98.3  3421.4    98.7  3451.4    98.4  3511.4    97.9  3601.4    97.5
  3681.4    95.4  3741.4    95.4  3791.4    95.5  3801.4    95.2  3971.4      98
  4131.4      98  4151.4    97.7  4161.4    97.9  4281.4    97.5  4431.4    96.2
  4491.4    96.2  4511.4    95.8  4701.4      95  4721.4    94.3    4740    94.3
  4758.7   94.08  4759.7   94.11  4761.1   94.14  4769.9   93.71  4770.2   93.26
  4784.5   93.78  4799.2   93.33  4799.7   93.79  4817.3   93.72  4817.9   93.72
  4869.9   94.45  4871.1   94.47  4921.3   94.15  4922.9   94.37 4935.19   94.24
  4935.3   94.24 4935.41   94.23  4954.3   94.03  4967.4   92.49  4967.7   92.37
  4983.8   85.66  4989.4   84.35  4991.2   82.55  4991.8   82.11  5000.3   81.88
  5001.4   81.85  5007.4   82.23  5008.8   82.84  5011.8   84.43    5022   89.56
  5028.3   91.54  5036.6   94.14  5058.9   94.23 5058.99   94.23  5059.1   94.23
 5059.21   94.23  5082.3   94.32  5083.4   94.32  5139.1   94.68  5139.4   94.68
  5178.8   94.25  5189.5   94.13  5189.7   94.13  5199.2   94.14  5199.7   93.68
  5214.3    94.2  5228.6   93.85  5229.2   94.29  5239.6   94.47  5239.7   94.48
  5243.1    94.8  5243.7   94.91  5246.5    95.4  5336.5    96.4  5366.5    95.7
  5536.5    97.6  5546.5    98.1  5636.5    97.9  5656.5    96.9  5696.5    98.2
  5756.5    98.2  5786.5      97  5806.5    96.8  5876.5    98.3  6166.5    99.1
  6196.5    98.8  6266.5    99.1  6296.5    98.3  6346.5      99  6446.5    98.2
  6476.5    96.9    6500   97.06  6506.5    97.1  6526.5    97.6  6606.5    97.5
  6626.5      98  6636.5    97.8  6726.5    99.3  6796.5    97.7  6836.5   100.5
  6906.5   101.4  6926.5   101.1  7086.5   101.4  7136.5    99.9  7156.5    99.4
  7166.5    98.8  7216.5    99.4  7236.5    98.9  7246.5    99.1  7256.5   100.1
  7296.5   101.1  7446.5   100.7  7536.5   100.5  7846.5   101.2  7856.5   100.7
  7936.5   101.2  7956.5   101.1  7976.5   101.3  8056.5   101.5  8116.5   102.1
  8236.5   101.9  8276.5   100.7  8286.5    99.7  8306.5    99.4  8316.5    99.9
  8346.5   102.2  8426.5     103  8456.5   102.1  8457.5   102.1
BR U #Mann= 6
  1361.4     .14  2941.4      .1 4935.19    .045  4954.3     .04  5036.6    .045
 5059.21      .1
BR U Banks=4954.3,5036.6
BR D #Sta/Elev= 159
  1361.4  105.34  1381.4  104.44  1551.4  103.64  1671.4  100.54  1981.4  100.44
  2011.4  100.84  2061.4  100.14  2081.4  100.94  2101.4  100.94  2121.4  100.14
  2131.4  100.24  2141.4  100.74  2301.4   99.14  2371.4   99.54  2411.4   98.74
  2461.4   98.74  2611.4   98.24  2621.4   97.94  2661.4   98.84  2811.4   98.04
  2921.4   98.74  2941.4   99.74  3021.4   99.84  3081.4   97.24  3101.4   97.24
  3121.4   98.54  3141.4   98.94  3161.4   98.74  3281.4   99.34  3301.4   98.74
  3371.4   98.24  3421.4   98.64  3451.4   98.34  3511.4   97.84  3601.4   97.44
  3681.4   95.34  3741.4   95.34  3791.4   95.44  3801.4   95.14  3971.4   97.94
  4131.4   97.94  4151.4   97.64  4161.4   97.84  4281.4   97.44  4431.4   96.14
  4491.4   96.14  4511.4   95.74  4701.4   94.94  4721.4   94.24    4740   94.24
  4758.7   94.02  4759.7   94.05  4761.1   94.08  4769.9   93.65  4770.2    93.2
  4784.5   93.72  4799.2   93.27  4799.7   93.73  4817.3   93.66  4817.9   93.66
  4869.9   94.39  4871.1   94.41  4921.3   94.09  4922.9   94.31 4935.19   94.18
  4935.3   94.18 4935.41   94.17  4954.3   93.97  4967.4   92.43  4967.7   92.31
  4983.8    85.6  4989.4   84.29  4991.2   82.49  4991.8   82.05  5000.3   81.82
  5001.4   81.79  5007.4   82.17  5008.8   82.78  5011.8   84.37    5022    89.5
  5028.3   91.48  5036.6   94.08  5058.9   94.17 5058.99   94.17  5059.1   94.17
 5059.21   94.17  5082.3   94.26  5083.4   94.26  5139.1   94.62  5139.4   94.62
  5178.8   94.19  5189.5   94.07  5189.7   94.07  5199.2   94.08  5199.7   93.62
  5214.3   94.14  5228.6   93.79  5229.2   94.23  5239.6   94.41  5239.7   94.42
  5243.1   94.74  5243.7   94.85  5246.5   95.34  5336.5   96.34  5366.5   95.64
  5536.5   97.54  5546.5   98.04  5636.5   97.84  5656.5   96.84  5696.5   98.14
  5756.5   98.14  5786.5   96.94  5806.5   96.74  5876.5   98.24  6166.5   99.04
  6196.5   98.74  6266.5   99.04  6296.5   98.24  6346.5   98.94  6446.5   98.14
  6476.5   96.84    6500      97  6506.5   97.04  6526.5   97.54  6606.5   97.44
  6626.5   97.94  6636.5   97.74  6726.5   99.24  6796.5   97.64  6836.5  100.44
  6906.5  101.34  6926.5  101.04  7086.5  101.34  7136.5   99.84  7156.5   99.34
  7166.5   98.74  7216.5   99.34  7236.5   98.84  7246.5   99.04  7256.5  100.04
  7296.5  101.04  7446.5  100.64  7536.5  100.44  7846.5  101.14  7856.5  100.64
  7936.5  101.14  7956.5  101.04  7976.5  101.24  8056.5  101.44  8116.5  102.04
  8236.5  101.84  8276.5  100.64  8286.5   99.64  8306.5   99.34  8316.5   99.84
  8346.5  102.14  8426.5  102.94  8456.5  102.04  8457.5  102.04
BR D #Mann= 6
  1361.4     .14  2941.4      .1 4935.19    .045  4954.3     .04  5036.6    .045
 5059.21      .1
BR D Banks=4954.3,5036.6
BC Design=,, 0 ,, 0 ,,,,,,
BC HTab HWMax=105.45

Type RM Length L Ch R = 1 ,10531.8 ,107,107.8,108
BEGIN DESCRIPTION:
Downstream Section of Bridge/Culvert/Weir
END DESCRIPTION:
XS GIS Cut Line= 6
      3120786.13     13951478.21      3118549.43     13948942.44
      3118398.55     13948842.69      3118288.27     13948769.16
      3118124.72     13948661.97      3115478.97      13946842.8
#Sta/Elev= 30
  1361.4   105.3  1671.4   100.5  2621.4    97.9  2941.4    99.7  3081.4    97.2
  3421.4    98.6  3681.4    95.3  4131.4    97.9  4770.2   93.16 4935.19   94.14
  4954.3   93.93  4967.4   92.39  4991.8   82.01  5001.4   81.75  5007.4   82.13
  5036.6   94.04 5059.21   94.13  5228.6   93.75  5546.5      98  6476.5    96.8
  6726.5    99.2  6796.5    97.6  6906.5   101.3  7086.5   101.3  7166.5    98.7
  7296.5     101  8116.5     102  8306.5    99.3  8346.5   102.1  8457.5     102
#Mann= 6 ,-1 , 0
  1361.4      .2       0  2941.4      .1       0 4935.19    .045       0
  4954.3     .04       0  5036.6    .045       0 5059.21      .1       0
#XS Ineff= 2 , 0
       0  4981.2   88.84  5019.6       0   88.84
Permanent Ineff=
       F       F
Bank Sta=4954.3,5036.6
XS Rating Curve= 0
Exp/Cntr=.5,.3

Type RM Length L Ch R = 1 ,10423.9 ,863,863.9,865
BEGIN DESCRIPTION:
K112-00-00-S6_HICKORY GATE DR - DS - XS 1
LIDAR overbanks - interpolated channel
END DESCRIPTION:
XS GIS Cut Line= 6
      3120850.24     13951391.67      3118613.54      13948855.9
      3118462.66     13948756.15      3118352.37     13948682.62
      3118188.82     13948575.43      3115543.08     13946756.26
#Sta/Elev= 30
  1351.6   104.2  1791.6  100.49  2961.6   97.72  3601.6   99.44  3721.6   96.38
  3861.6   98.45  4081.6   95.43  4321.6   96.77  4491.6   94.26  4641.6   95.99
  4912.9   95.12  4963.7   90.62  4983.7   86.08 4991.83   82.05 5001.18   81.38
  5043.7    91.9  5086.3   94.81  5641.8   98.81  5801.8   97.19  5861.8   99.57
  6011.8  100.43  6711.8  100.32  6951.8   97.66  7161.8  101.33  7241.8   98.86
  7431.8   98.58  8141.8  100.85  8311.8   99.23  8371.8  102.69  8452.7  101.91
#Mann= 5 ,-1 , 0
  1351.6      .2       0  2961.6      .1       0  4912.9     .04       0
  5086.3     .14       0  5641.8      .1       0
Bank Sta=4912.9,5086.3
XS Rating Curve= 0
Exp/Cntr=.3,.1

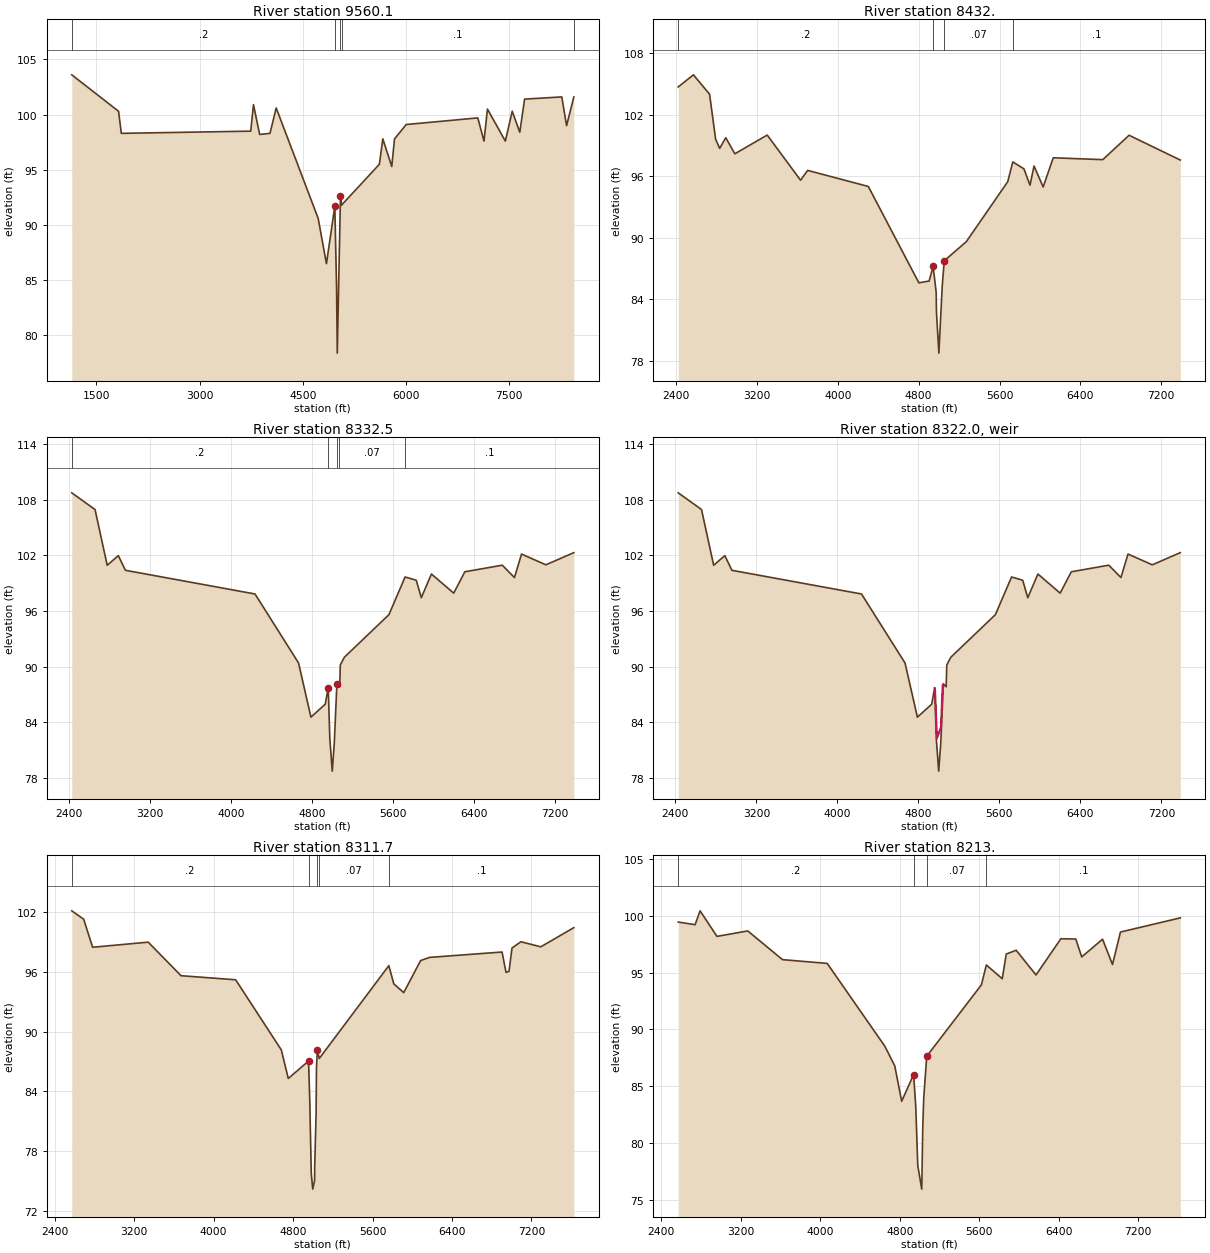
Type RM Length L Ch R = 1 ,9560.1  ,1128.1,1128.1,1127
BEGIN DESCRIPTION:
Cross Section K112-00-00-X6
END DESCRIPTION:
XS GIS Cut Line= 4
      3121665.99     13950675.67      3118923.77     13948027.12
      3118844.55     13947971.46      3115926.14      13946256.1
#Sta/Elev= 30
  1141.9   103.6  1821.9   100.3  1861.9    98.3  3741.9    98.5  3781.9   100.9
  3871.9    98.2  4021.9    98.3  4111.9   100.6  4721.9    90.6  4841.9    86.5
  4963.6   91.69    4989   84.38  4999.4    78.4  5045.7   92.59  5061.1    91.8
  5611.1    95.5  5661.1    97.8  5791.1    95.3  5831.1    97.8  6001.1    99.1
  7041.1    99.7  7131.1    97.6  7181.1   100.5  7441.1    97.6  7541.1   100.3
  7651.1    98.4  7721.1   101.4  8261.1   101.6  8331.1      99  8436.4   101.6
#Mann= 5 ,-1 , 0
  1141.9      .2       0  4963.6     .04       0  5045.7    .045       0
  5061.1      .1       0  8436.4      .2       0
Bank Sta=4963.6,5045.7
XS Rating Curve= 0
Exp/Cntr=.3,.1

Type RM Length L Ch R = 1 ,8432.   ,99.5,99.5,66
BEGIN DESCRIPTION:
K112-00-00-S5_DAM - US - XS 4
LIDAR overbanks - interpolated channel
END DESCRIPTION:
XS GIS Cut Line= 4
      3121100.03     13949109.48      3119605.81     13947128.61
      3119461.53     13947024.61      3117161.57     13946849.34
#Sta/Elev= 30
  2422.5  104.72  2572.5   105.9  2732.5  104.01  2792.5    99.6  2832.5   98.72
  2892.5   99.76  2982.5   98.19  3302.5  100.02  3632.5   95.61  3702.5   96.57
  4302.5      95  4802.5   85.59  4903.7   85.77  4943.7   87.19  4973.7   84.66
  4976.6    82.7 5000.32   78.73  5033.7   85.32  5053.7   87.75  5271.6   89.61
  5681.6   95.47  5731.6    97.4  5841.6   96.72  5901.6   95.13  5941.6      97
  6031.6   94.95  6131.6    97.8  6621.6   97.62  6881.6     100  7388.2   97.58
#Mann= 4 ,-1 , 0
  2422.5      .2       0  4943.7     .04       0  5053.7     .07       0
  5731.6      .1       0
Bank Sta=4943.7,5053.7
XS Rating Curve= 0
Exp/Cntr=.7,.5

Type RM Length L Ch R = 1 ,8332.5  ,20.8,20.8,20.8
BEGIN DESCRIPTION:
Upstream Section of Bridge/Culvert/Weir
END DESCRIPTION:
XS GIS Cut Line= 4
      3121151.31     13949019.73      3119610.32     13946999.27
      3119550.77     13946960.41      3117212.85     13946759.59
#Sta/Elev= 30
  2427.9  108.72  2657.9  106.92  2777.9  100.92  2887.9  101.96  2957.9  100.38
  4237.9   97.83  4667.9    90.4    4790   84.57  4931.7   85.97  4960.8   87.75
  4976.5   82.28  5000.4   78.76  5021.1   81.85  5046.2   88.13  5062.6   87.96
  5074.1   87.84  5080.1   90.19  5120.1   91.02  5560.1    95.6  5720.1   99.66
  5830.1   99.31  5880.1   97.43  5980.1   99.98  6200.1   97.92  6310.1  100.22
  6680.1  100.93  6800.1    99.6  6870.1  102.13  7110.1  100.97  7386.6  102.28
#Mann= 5 ,-1 , 0
  2427.9      .2       0  4960.8     .04       0  5046.2    .045       0
  5062.6     .07       0  5720.1      .1       0
#XS Ineff= 2 , 0
       0  4960.8    85.5    5042       0      86
Permanent Ineff=
       F       F
Bank Sta=4960.8,5046.2
XS Rating Curve= 0
Exp/Cntr=.7,.5

Type RM Length L Ch R = 5 ,8322.0  ,,,
BEGIN DESCRIPTION:
Structure ID: K112-00-00-S5 - 1000' US REYNALDO DRIVE
END DESCRIPTION:
IW Pilot Flow=0
#Inline Weir SE= 16
  4960.8   87.68  4965.2   87.26  4976.5   84.22  4978.9   83.57  4983.1    82.3
  4989.1   82.48  4991.1   82.54  4992.5   82.58  5000.4   82.82  5008.8   83.08
  5011.8   83.17  5021.1   83.45  5022.4   83.49  5039.2   87.94  5039.7   88.07
 5046.0788.11616
IW Dist,WD,Coef,Skew,MaxSub,Min_El,Is_Ogee,SpillHt,DesHd
10,1,3,0,.95,, 0 ,,,0,0,

Type RM Length L Ch R = 1 ,8311.7  ,99,98.7,97.7
BEGIN DESCRIPTION:
Cross Section FIELD_DS for K112-00-00-S5 - 1000' US REYNALDO DRIVE
END DESCRIPTION:
XS GIS Cut Line= 4
      3121293.51     13948701.76      3119634.75     13946992.29
      3119534.38     13946925.63      3117041.77     13946374.49
#Sta/Elev= 30
  2571.7  102.14  2691.7   101.3  2781.7   98.48  3341.7   98.99  3671.7   95.62
  4221.7   95.21  4681.7   88.16  4751.7   85.29  4955.8   87.04  4967.8    83.2
  4983.2   75.76    4998   74.17    5017   75.05  5017.5   76.39  5031.8   81.74
  5035.4    86.3  5044.4   88.11  5063.7    87.3  5764.2   96.63  5814.2    94.8
  5914.2   93.92  6084.2   97.14  6174.2   97.46  6904.2      98  6944.2   95.95
  6974.2   96.06  7004.2    98.4  7094.2   99.03  7294.2   98.52    7627  100.45
#Mann= 5 ,-1 , 0
  2571.7      .2       0  4955.8     .04       0  5044.4    .045       0
  5063.7     .07       0  5764.2      .1       0
#XS Ineff= 2 , 0
       0    4929    85.2               0
Permanent Ineff=
       F       F
Bank Sta=4955.8,5044.4
XS Rating Curve= 0
Exp/Cntr=.7,.5

Type RM Length L Ch R = 1 ,8213.   ,455,448,443
BEGIN DESCRIPTION:
K112-00-00-S5_DAM - DS - XS 1
LIDAR overbanks - interpolated channel
END DESCRIPTION:
XS GIS Cut Line= 4
       3121344.8     13948624.83      3119686.03     13946915.36
      3119585.67     13946848.71      3117093.05     13946297.56
#Sta/Elev= 30
    2570   99.45    2740   99.22    2790  100.44    2960   98.19    3270   98.67
    3620   96.14    4070   95.81    4650   88.52    4750   86.79    4820   83.67
    4940   86.02    4962   83.14    4982      78    5022   75.93    5032   81.35
    5042   83.98    5072   87.63  5622.5   93.92  5672.5   95.67  5832.5   94.46
  5872.5   96.63  5972.5   96.97  6172.5   94.79  6422.5   97.98  6572.5   97.96
  6632.5   96.38  6842.5   97.94  6942.5   95.71  7022.5   98.57  7625.3   99.82
#Mann= 4 ,-1 , 0
    2570      .2       0    4940     .04       0    5072     .07       0
  5672.5      .1       0
Bank Sta=4940,5072
XS Rating Curve= 0
Exp/Cntr=.3,.1

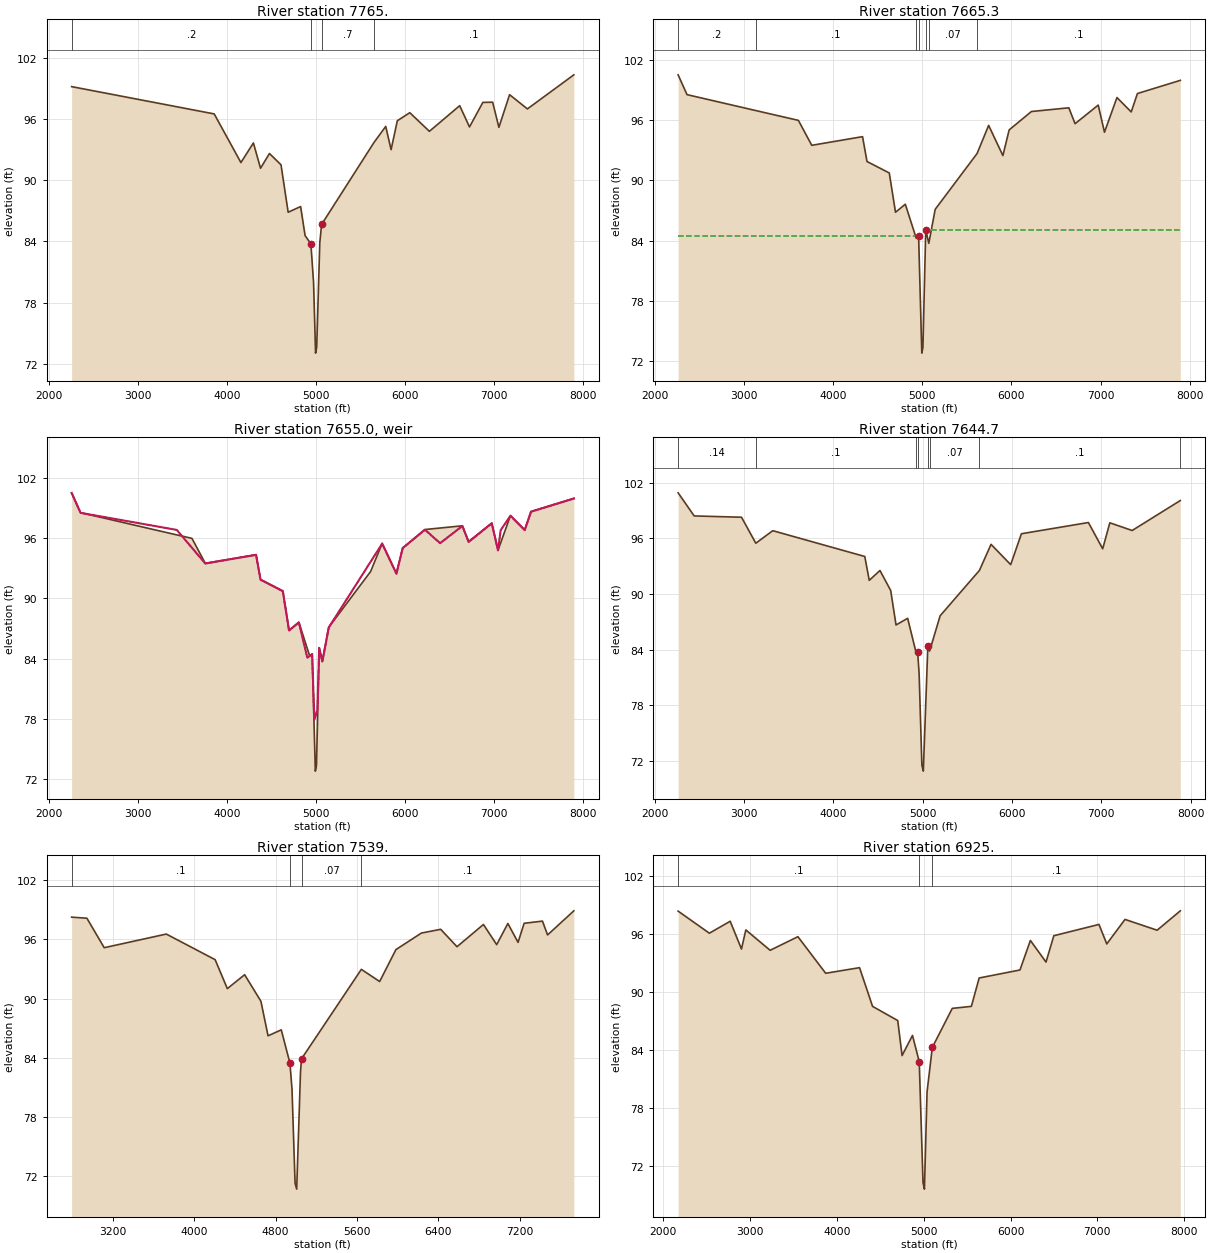
Type RM Length L Ch R = 1 ,7765.   ,100,99.7,98.7
BEGIN DESCRIPTION:
K112-00-00-S4_DAM - US - XS 4
LIDAR overbanks - interpolated channel
END DESCRIPTION:
XS GIS Cut Line= 4
      3121689.91     13948584.91      3119942.08     13946546.45
      3119848.45     13946488.53      3117024.18     13946179.31
#Sta/Elev= 30
  2257.1   99.21  3857.1   96.53  4157.1   91.75  4297.1   93.68  4377.1   91.19
  4477.1   92.64  4607.1   91.53  4687.1   86.87  4827.1   87.43  4877.1   84.58
  4942.3   83.76  4972.3   79.96 4994.79   73.03 5007.48   73.59  5042.3   83.89
  5062.4   85.67  5652.4   93.75  5782.4    95.3  5842.4   93.02  5912.4   95.86
  6052.4   96.65  6272.4   94.82  6612.4   97.34  6722.4   95.25  6872.4   97.66
  6982.4   97.68  7052.4   95.21  7172.4   98.42  7372.4   97.02  7893.5  100.37
#Mann= 4 ,-1 , 0
  2257.1      .2       0  4942.3     .04       0  5062.4      .7       0
  5652.4      .1       0
Bank Sta=4942.3,5062.4
XS Rating Curve= 0
Exp/Cntr=.7,.5

Type RM Length L Ch R = 1 ,7665.3  ,20.6,20.6,20.6
BEGIN DESCRIPTION:
Upstream Section of Bridge/Culvert/Weir
END DESCRIPTION:
XS GIS Cut Line= 4
       3121741.2     13948498.37      3119993.36     13946459.91
      3119899.73     13946401.99      3117075.46     13946092.77
#Sta/Elev= 30
  2259.1   100.5  2359.1   98.53  3129.1   96.95  3609.1   95.97  3759.1   93.49
  4329.1   94.35  4379.1   91.88  4629.1   90.74  4699.1   86.83  4809.1   87.63
  4931.9   84.24  4958.4   84.48  4994.2   72.82  5006.8   73.37  5038.4    85.1
  5072.8   83.74  5144.4   87.12  5614.4   92.67  5744.4   95.47  5904.4   92.47
  5974.4   95.02  6224.4   96.85  6644.4   97.22  6714.4   95.64  6974.4   97.49
  7044.4   94.79  7184.4   98.24  7344.4   96.81  7414.4   98.64  7895.5   99.95
#Mann= 7 ,-1 , 0
  2259.1      .2       0  3129.1      .1       0  4931.9    .045       0
  4958.4     .04       0  5038.4    .045       0  5072.8     .07       0
  5614.4      .1       0
#XS Ineff= 2 , 0
       0  4948.4   84.42  5048.4       0   85.06
Permanent Ineff=
       F       F
Bank Sta=4958.4,5038.4
XS Rating Curve= 0
Exp/Cntr=.7,.5

Type RM Length L Ch R = 5 ,7655.0  ,,,
BEGIN DESCRIPTION:
Structure ID: K112-00-00-S4 - 600FT US REYNALDO DRIVE
END DESCRIPTION:
IW Pilot Flow=0
#Inline Weir SE= 30
  2259.1  100.48  2359.1   98.51  3439.1   96.81  3759.1   93.47  4329.1   94.33
  4379.1   91.86  4629.1   90.72  4699.1   86.81  4809.1   87.61    4904   84.11
  4958.4   84.46  4983.4   77.95  5016.5   78.86  5037.2   85.07  5072.8   83.72
  5144.4    87.1  5744.4   95.45  5904.4   92.45  5974.4      95  6224.4   96.83
  6394.4   95.49  6644.4    97.2  6714.4   95.62  6974.4   97.47  7044.4   94.77
  7074.4   96.79  7184.4   98.22  7344.4   96.79  7414.4   98.62  7895.5   99.93
IW Dist,WD,Coef,Skew,MaxSub,Min_El,Is_Ogee,SpillHt,DesHd
10,.6,3,0,.95,, 0 ,,,0,0,

Type RM Length L Ch R = 1 ,7644.7  ,101.9,105.7,109
BEGIN DESCRIPTION:
Cross Section FIELD_DS K112-00-00-S4 600FT US REYNALDO DRIVE
Located At:
END DESCRIPTION:
XS GIS Cut Line= 5
      3121804.07     13948432.71      3120006.17     13946442.03
      3119918.09     13946387.45      3119885.59     13946368.43
      3117104.78      13946049.5
#Sta/Elev= 30
  2262.4   100.9  2442.4   98.41  2972.4   98.27  3132.4   95.47  3322.4   96.82
  4352.4   94.04  4402.4   91.47  4522.4   92.53  4642.4   90.38  4702.4   86.66
  4832.4   87.38  4922.4   83.86  4944.7   83.71  4944.8    83.7    4961   81.37
  4991.8   71.55  5007.9   70.91  5058.3   84.36  5058.4   84.36  5078.4   83.85
  5196.1   87.65  5636.1   92.54  5766.1   95.35  5986.1   93.16  6106.1   96.49
  6856.1    97.7  7016.1   94.87  7096.1   97.67  7346.1   96.84  7885.1  100.07
#Mann= 8 ,-1 , 0
  2262.4     .14       0  3132.4      .1       0  4922.4    .045       0
  4944.7     .04       0  5058.3    .045       0  5078.4     .07       0
  5636.1      .1       0  7885.1      .2       0
Bank Sta=4944.8,5058.4
XS Rating Curve= 0
Exp/Cntr=.7,.5

Type RM Length L Ch R = 1 ,7539.   ,592.3,614,637.3
BEGIN DESCRIPTION:
K112-00-00-S4_DAM - DS - XS 1
LIDAR overbanks - interpolated channel
END DESCRIPTION:
XS GIS Cut Line= 5
      3121462.21     13947982.66      3120063.86     13946355.49
      3119975.79     13946300.91      3119943.28     13946281.89
      3117385.08     13945597.27
#Sta/Elev= 30
  2796.4   98.23  2946.4   98.12  3116.4   95.14  3726.4   96.52  4206.4   93.93
  4326.4      91  4496.4   92.41  4656.4   89.72  4726.4   86.23  4856.4   86.83
  4941.9   83.45  4961.9   80.81 4991.97   71.32  5007.9   70.72  5045.5   82.61
  5055.5    83.9  5643.2   92.95  5823.2   91.72  5983.2   94.95  6233.2   96.62
  6423.2      97  6583.2   95.24  6843.2   97.49  6973.2   95.45  7083.2   97.59
  7183.2   95.68  7243.2   97.61  7423.2   97.83  7473.2   96.43  7731.4   98.87
#Mann= 4 ,-1 , 0
  2796.4      .1       0  4941.9     .04       0  5055.5     .07       0
  5643.2      .1       0
Bank Sta=4941.9,5055.5
XS Rating Curve= 0
Exp/Cntr=.3,.1

Type RM Length L Ch R = 1 ,6925.   ,83,99.2,119
BEGIN DESCRIPTION:
K112-00-00-S3_REYNALDO - US - XS 4
LIDAR overbanks - interpolated channel
END DESCRIPTION:
XS GIS Cut Line= 4
       3121696.7     13948244.38      3120374.77      13945858.3
      3120238.88     13945724.87      3117385.93     13945441.53
#Sta/Elev= 30
  2170.4    98.4  2530.4   96.11  2770.4   97.35  2900.4   94.47  2950.4   96.45
  3230.4   94.34  3550.4   95.75  3870.4   91.96  4260.4   92.54  4410.4   88.53
  4700.4   87.06  4750.4   83.43  4870.4   85.52  4948.2    82.8 4991.63   70.28
  5007.9   69.59  5038.2   79.67  5098.6   84.27  5328.6   88.32  5548.6   88.53
  5638.6   91.47  6108.6    92.3  6228.6   95.36  6408.6   93.12  6498.6   95.85
  7018.6   97.02  7108.6      95  7318.6   97.54  7688.6   96.42  7955.6   98.43
#Mann= 3 ,-1 , 0
  2170.4      .1       0  4948.2     .04       0  5098.6      .1       0
Bank Sta=4948.2,5098.6
XS Rating Curve= 0
Exp/Cntr=.5,.3