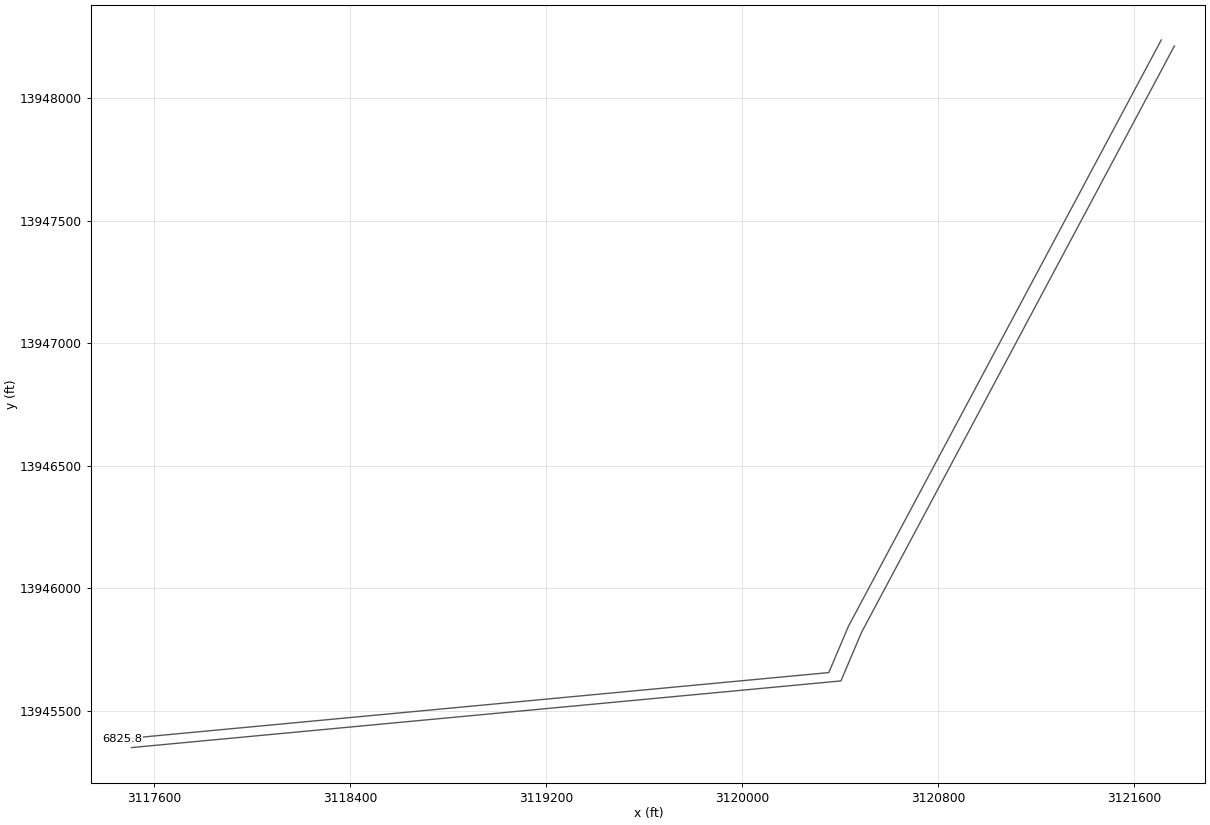
HEC-RAS study K112-00-00.prj: K112-00-00

--- K112-00-00.g01 (geometry) --- (continued)

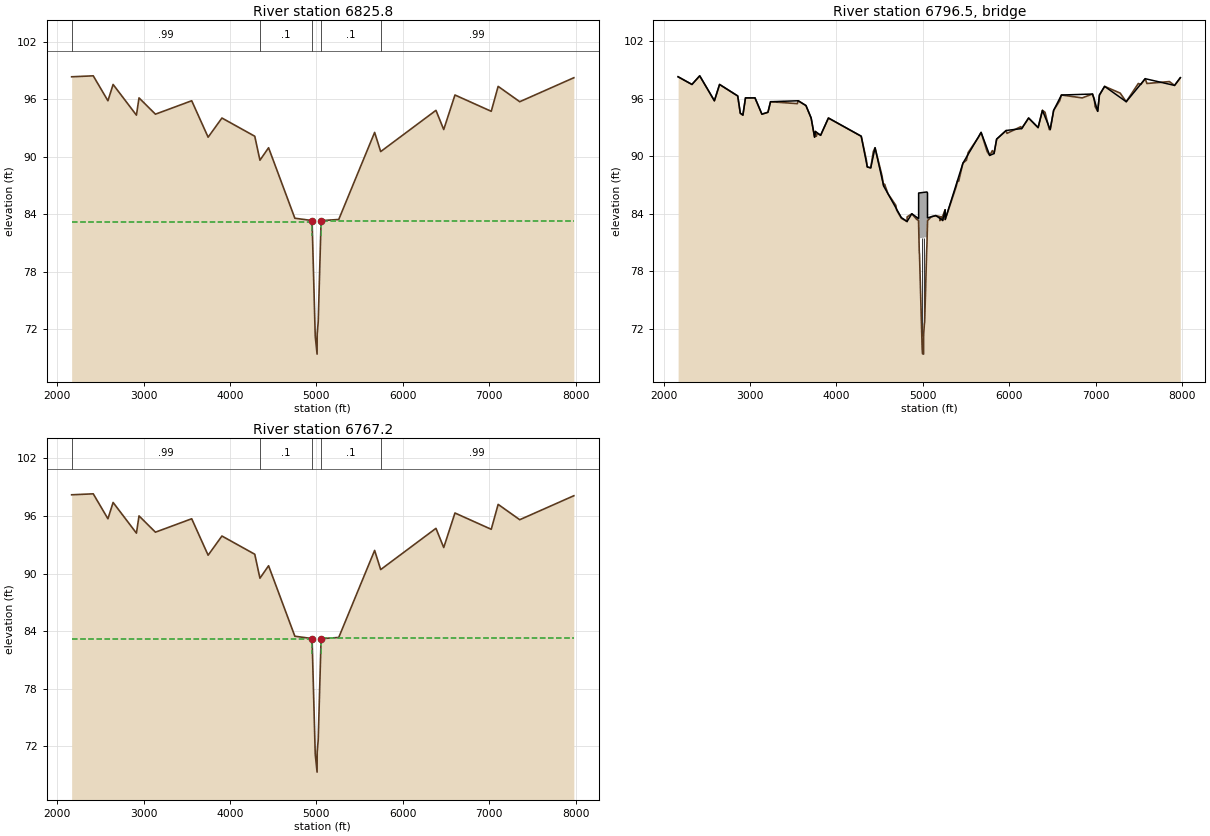
Type RM Length L Ch R = 1 ,6825.8  ,58.6,58.6,58.6
BEGIN DESCRIPTION:
Upstream Section of Bridge/Culvert/Weir
END DESCRIPTION:
XS GIS Cut Line= 4
      3121709.83     13948236.98      3120432.37     13945842.61
      3120352.89     13945654.82      3117469.27     13945383.83
#Sta/Elev= 30
  2166.4   98.33  2416.4   98.43  2586.4   95.83  2646.4   97.53  2916.4   94.33
  2946.4   96.13  3136.4   94.43  3556.4   95.83  3746.4   92.03  3906.4   94.03
  4286.4   92.13  4346.4   89.63  4446.4   90.93  4750.7   83.58  4949.9   83.34
  4986.6   71.29  5007.9   69.41    5009   71.46    5021   72.78  5054.5   83.33
  5258.7   83.45  5674.2   92.53  5744.2   90.53  6384.2   94.83  6474.2   92.83
  6604.2   96.43  7024.2   94.73  7104.2   97.33  7354.2   95.73  7980.5   98.23
#Mann= 5 ,-1 , 0
  2166.4     .99       0  4346.4      .1       0  4949.9     .04       0
  5054.5      .1       0  5744.2     .99       0
#XS Ineff= 2 , 0
       0 4954.81   83.21 5049.45       0   83.31
Permanent Ineff=
       F       F
Bank Sta=4949.9,5054.5
XS Rating Curve= 0
Exp/Cntr=.5,.3

Type RM Length L Ch R = 3 ,6796.5  ,,,
BEGIN DESCRIPTION:
REYNALDO DRIVE
Structure ID: K112-00-00-S3
END DESCRIPTION:
Bridge Culvert--1,0,-1,-1, 0
Deck Dist Width WeirC Skew NumUp NumDn MinLoCord MaxHiCord MaxSubmerge Is_Ogee
10,38.6,2.6,0, 60, 60, , , .95, 0, ,,,
  2166.4  2326.4  2416.4  2586.4  2646.4  2856.4  2886.4  2916.4  2946.4  3056.4
  3136.4  3206.4  3236.4  3556.4  3646.4  3706.4  3746.4  3756.4  3816.4  3906.4
  4286.4  4356.4  4396.4  4446.4  4546.4  4750.7  4817.3  4872.2  4949.2 4950.79
  4950.9    5047 5053.59  5053.7 5053.81  5149.8  5229.7  5257.7  5258.7  5464.2
  5674.2  5774.2  5824.2  5854.2  5964.2  6144.2  6224.2  6334.2  6384.2  6474.2
  6514.2  6604.2  6964.2  7024.2  7044.2  7104.2  7354.2  7574.2  7914.2  7980.5
    98.3    97.5    98.4    95.8    97.5    96.3    94.5    94.3    96.1    96.1
    94.4    94.6    95.7    95.8    95.3      94      92    92.6    92.2      94
    92.1    88.9    88.8    90.9    86.9   83.62   83.21   84.02   83.52   83.58
   86.18   86.29   86.19   86.19   83.59   83.83   83.33   84.43   83.42    89.3
    92.5    90.1    90.3    91.8    92.7    92.9      94      93    94.8    92.8
    94.8    96.4    96.5    94.7    96.4    97.3    95.7    98.1    97.4    98.2
    98.3    97.5    98.4    95.8    97.5    96.3    94.5    94.3    96.1    96.1
    94.4    94.6    95.7    95.8    95.3      94      92    92.6    92.2      94
    92.1    88.9    88.8    90.9    86.9   83.55    83.2   84.01   83.31   82.97
   81.44   81.58   81.58   83.03   83.06   83.82    83.3   84.43   83.42    89.3
    92.5    90.1    90.3    91.8    92.7    92.9      94      93    94.8    92.8
    94.8    96.4    96.5    94.7    96.4    97.3    95.7    98.1    97.4    98.2
  2166.4  2326.4  2416.4  2586.4  2646.4  2856.4  2886.4  2916.4  2946.4  3056.4
  3136.4  3206.4  3236.4  3556.4  3646.4  3706.4  3746.4  3756.4  3816.4  3906.4
  4286.4  4356.4  4396.4  4446.4  4546.4  4750.7  4817.3  4872.2  4949.2 4950.79
  4950.9    5047 5053.59  5053.7 5053.81  5149.8  5229.7  5257.7  5258.7  5464.2
  5674.2  5774.2  5824.2  5854.2  5964.2  6144.2  6224.2  6334.2  6384.2  6474.2
  6514.2  6604.2  6964.2  7024.2  7044.2  7104.2  7354.2  7574.2  7914.2  7980.5
    98.3    97.5    98.4    95.8    97.5    96.3    94.5    94.3    96.1    96.1
    94.4    94.6    95.7    95.8    95.3      94      92    92.6    92.2      94
    92.1    88.9    88.8    90.9    86.9   83.62   83.21   84.02   83.52   83.58
   86.18   86.29   86.19   86.19   83.59   83.83   83.33   84.43   83.42    89.3
    92.5    90.1    90.3    91.8    92.7    92.9      94      93    94.8    92.8
    94.8    96.4    96.5    94.7    96.4    97.3    95.7    98.1    97.4    98.2
   98.23   97.43   98.33   95.73   97.43   96.23   94.43   94.23   96.03   96.03
   94.33   94.53   95.63   95.73   95.23   93.93   91.93   92.53   92.13   93.93
   92.03   88.83   88.73   90.83   86.83   83.48   83.13   83.94   83.24    82.9
   81.37   81.51   81.51   82.96   82.99   83.75   83.23   84.36   83.35   89.23
   92.43   90.03   90.23   91.73   92.63   92.83   93.93   92.93   94.73   92.73
   94.73   96.33   96.43   94.63   96.33   97.23   95.63   98.03   97.33   98.13
Pier Skew, UpSta & Num, DnSta & Num=  ,4986.6, 2 ,4986.6, 2 , 0 , 0 , 0 ,,
     1.2     1.2
   70.18   82.63
     1.2     1.2
   70.11   82.56
Pier Skew, UpSta & Num, DnSta & Num=  ,5017.7, 2 ,5017.7, 2 , 0 , 0 , 0 ,,
     1.2     1.2
   71.49   82.61
     1.2     1.2
   71.42   82.54
Abutment Skew #Up #Dn= , 2 , 2
  4945.1  4995.8
   83.34   69.42
  4945.1  4995.8
   83.27   69.35
Abutment Skew #Up #Dn= , 2 , 2
  5008.2 5049.49
   70.35   81.52
  5008.2 5049.49
   70.28   81.45
BR Coef= 1 , 1 , 1 ,1.25, 0 ,,,.8,0,2,0,
WSPro=,,,, 1 ,,,, 0 ,,,, 0 ,,,,-1 ,-1 ,-1 , 0 , 0 , 0 , 0 , 0
BR U #Sta/Elev= 145
  2166.4    98.3  2326.4    97.5  2416.4    98.4  2586.4    95.8  2646.4    97.5
  2856.4    96.3  2886.4    94.5  2916.4    94.3  2946.4    96.1  3056.4    96.1
  3136.4    94.4  3206.4    94.6  3236.4    95.7  3546.4    95.5  3556.4    95.8
  3646.4    95.3  3706.4      94  3746.4      92  3756.4    92.6  3766.4    92.1
  3776.4    92.4  3816.4    92.2  3906.4      94  4286.4    92.1  4346.4    89.6
  4356.4    88.9  4396.4    88.8  4426.4    90.5  4446.4    90.9  4526.4      88
  4546.4    86.9  4556.4    87.1  4596.4    86.1  4686.4    84.9  4696.4    84.4
  4724.1   83.97  4750.7   83.55  4750.8   83.55  4805.1   83.26  4807.8   83.25
  4817.3    83.2  4817.7   83.69  4872.2   84.01  4872.7   84.01  4924.1   83.48
  4927.7   83.44  4927.9   83.44 4945.21   83.34  4945.3   83.34  4949.2   83.31
  4949.9   83.31 4950.79   82.97  4950.9   82.93 4951.01   82.89 4951.12   82.85
  4957.4   80.45  4957.6   80.38  4957.7   80.34  4958.7   79.96    4961   79.84
  4975.9   75.06  4986.6   71.26  4987.2   71.18  4987.5    71.1  4991.8   70.02
    4995   69.42  4995.8   69.42  5001.2   69.42  5007.9   69.38  5008.1   70.22
  5008.2   70.35    5009   71.43  5017.1   72.49  5017.8   72.58    5021   72.75
  5035.4   77.52  5036.6    77.9  5043.3      80  5046.5   80.57    5047   80.74
 5047.11   80.78 5049.29   81.52  5049.4   81.56  5053.5   82.96 5053.59   82.99
  5053.7   83.03 5053.81   83.06  5054.5    83.3  5096.7   83.71  5097.6   83.71
  5149.8   83.82  5149.9   83.82  5196.5   83.72  5196.8    83.3  5201.8   83.44
  5212.1   83.72  5212.2   83.72  5229.7    83.3  5230.3   83.78  5256.2   84.39
  5257.7   84.43  5258.7   83.42  5384.2    86.8  5404.2    87.5  5414.2    87.4
  5464.2    89.3  5504.2    89.6  5524.2    90.4  5644.2      92  5674.2    92.5
  5744.2    90.5  5774.2    90.1  5804.2    90.6  5824.2    90.3  5854.2    91.8
  5964.2    92.7  5974.2    92.4  6134.2    93.1  6144.2    92.9  6224.2      94
  6334.2      93  6384.2    94.8  6414.2    94.6  6456.2   93.09  6464.2    92.8
  6474.2    92.8  6514.2    94.8  6584.2    95.8  6604.2    96.4  6844.2    96.1
  6964.2    96.5  6984.2      96  6994.2    95.2  7024.2    94.7  7044.2    96.4
  7104.2    97.3  7284.2    96.6  7354.2    95.7  7494.2    97.6  7524.2    97.5
  7574.2    98.1  7594.2    97.6  7854.2    97.8  7914.2    97.4  7980.5    98.2
BR U #Mann= 5
  2166.4     .99  4346.4      .1  4949.9     .04  5054.5      .1  5744.2     .99
BR U Banks=4949.9,5054.5
BR D #Sta/Elev= 145
  2166.4   98.23  2326.4   97.43  2416.4   98.33  2586.4   95.73  2646.4   97.43
  2856.4   96.23  2886.4   94.43  2916.4   94.23  2946.4   96.03  3056.4   96.03
  3136.4   94.33  3206.4   94.53  3236.4   95.63  3546.4   95.43  3556.4   95.73
  3646.4   95.23  3706.4   93.93  3746.4   91.93  3756.4   92.53  3766.4   92.03
  3776.4   92.33  3816.4   92.13  3906.4   93.93  4286.4   92.03  4346.4   89.53
  4356.4   88.83  4396.4   88.73  4426.4   90.43  4446.4   90.83  4526.4   87.93
  4546.4   86.83  4556.4   87.03  4596.4   86.03  4686.4   84.83  4696.4   84.33
  4724.1    83.9  4750.7   83.48  4750.8   83.48  4805.1   83.19  4807.8   83.18
  4817.3   83.13  4817.7   83.62  4872.2   83.94  4872.7   83.94  4924.1   83.41
  4927.7   83.37  4927.9   83.37 4945.21   83.27  4945.3   83.27  4949.2   83.24
  4949.9   83.24 4950.79    82.9  4950.9   82.86 4951.01   82.82 4951.12   82.78
  4957.4   80.38  4957.6   80.31  4957.7   80.27  4958.7   79.89    4961   79.77
  4975.9   74.99  4986.6   71.19  4987.2   71.11  4987.5   71.03  4991.8   69.95
    4995   69.35  4995.8   69.35  5001.2   69.35  5007.9   69.31  5008.1   70.15
  5008.2   70.28    5009   71.36  5017.1   72.42  5017.8   72.51    5021   72.68
  5035.4   77.45  5036.6   77.83  5043.3   79.93  5046.5    80.5    5047   80.67
 5047.11   80.71 5049.29   81.45  5049.4   81.49  5053.5   82.89 5053.59   82.92
  5053.7   82.96 5053.81   82.99  5054.5   83.23  5096.7   83.64  5097.6   83.64
  5149.8   83.75  5149.9   83.75  5196.5   83.65  5196.8   83.23  5201.8   83.37
  5212.1   83.65  5212.2   83.65  5229.7   83.23  5230.3   83.71  5256.2   84.32
  5257.7   84.36  5258.7   83.35  5384.2   86.73  5404.2   87.43  5414.2   87.33
  5464.2   89.23  5504.2   89.53  5524.2   90.33  5644.2   91.93  5674.2   92.43
  5744.2   90.43  5774.2   90.03  5804.2   90.53  5824.2   90.23  5854.2   91.73
  5964.2   92.63  5974.2   92.33  6134.2   93.03  6144.2   92.83  6224.2   93.93
  6334.2   92.93  6384.2   94.73  6414.2   94.53  6456.2   93.02  6464.2   92.73
  6474.2   92.73  6514.2   94.73  6584.2   95.73  6604.2   96.33  6844.2   96.03
  6964.2   96.43  6984.2   95.93  6994.2   95.13  7024.2   94.63  7044.2   96.33
  7104.2   97.23  7284.2   96.53  7354.2   95.63  7494.2   97.53  7524.2   97.43
  7574.2   98.03  7594.2   97.53  7854.2   97.73  7914.2   97.33  7980.5   98.13
BR D #Mann= 5
  2166.4     .99  4346.4      .1  4949.9     .04  5054.5      .1  5744.2     .99
BR D Banks=4949.9,5054.5
BC Design=,, 0 ,, 0 ,,,,,,
BC HTab HWMax=98.43

Type RM Length L Ch R = 1 ,6767.2  ,316,298.1,280
BEGIN DESCRIPTION:
Downstream Section of Bridge/Culvert/Weir
END DESCRIPTION:
XS GIS Cut Line= 4
       3121763.3     13948212.31      3120486.27     13945818.73
      3120402.48     13945620.77      3117506.97     13945348.66
#Sta/Elev= 30
  2166.4   98.21  2416.4   98.31  2586.4   95.71  2646.4   97.41  2916.4   94.21
  2946.4   96.01  3136.4   94.31  3556.4   95.71  3746.4   91.91  3906.4   93.91
  4286.4   92.01  4346.4   89.51  4446.4   90.81  4750.7   83.46  4949.9   83.22
  4986.6   71.17  5007.9   69.29    5009   71.34    5021   72.66  5054.5   83.21
  5258.7   83.33  5674.2   92.41  5744.2   90.41  6384.2   94.71  6474.2   92.71
  6604.2   96.31  7024.2   94.61  7104.2   97.21  7354.2   95.61  7980.5   98.11
#Mann= 5 ,-1 , 0
  2166.4     .99       0  4346.4      .1       0  4949.9     .04       0
  5054.5      .1       0  5744.2     .99       0
#XS Ineff= 2 , 0
       0 4954.81   83.21 5049.45       0   83.31
Permanent Ineff=
       F       F
Bank Sta=4949.9,5054.5
XS Rating Curve= 0
Exp/Cntr=.5,.3