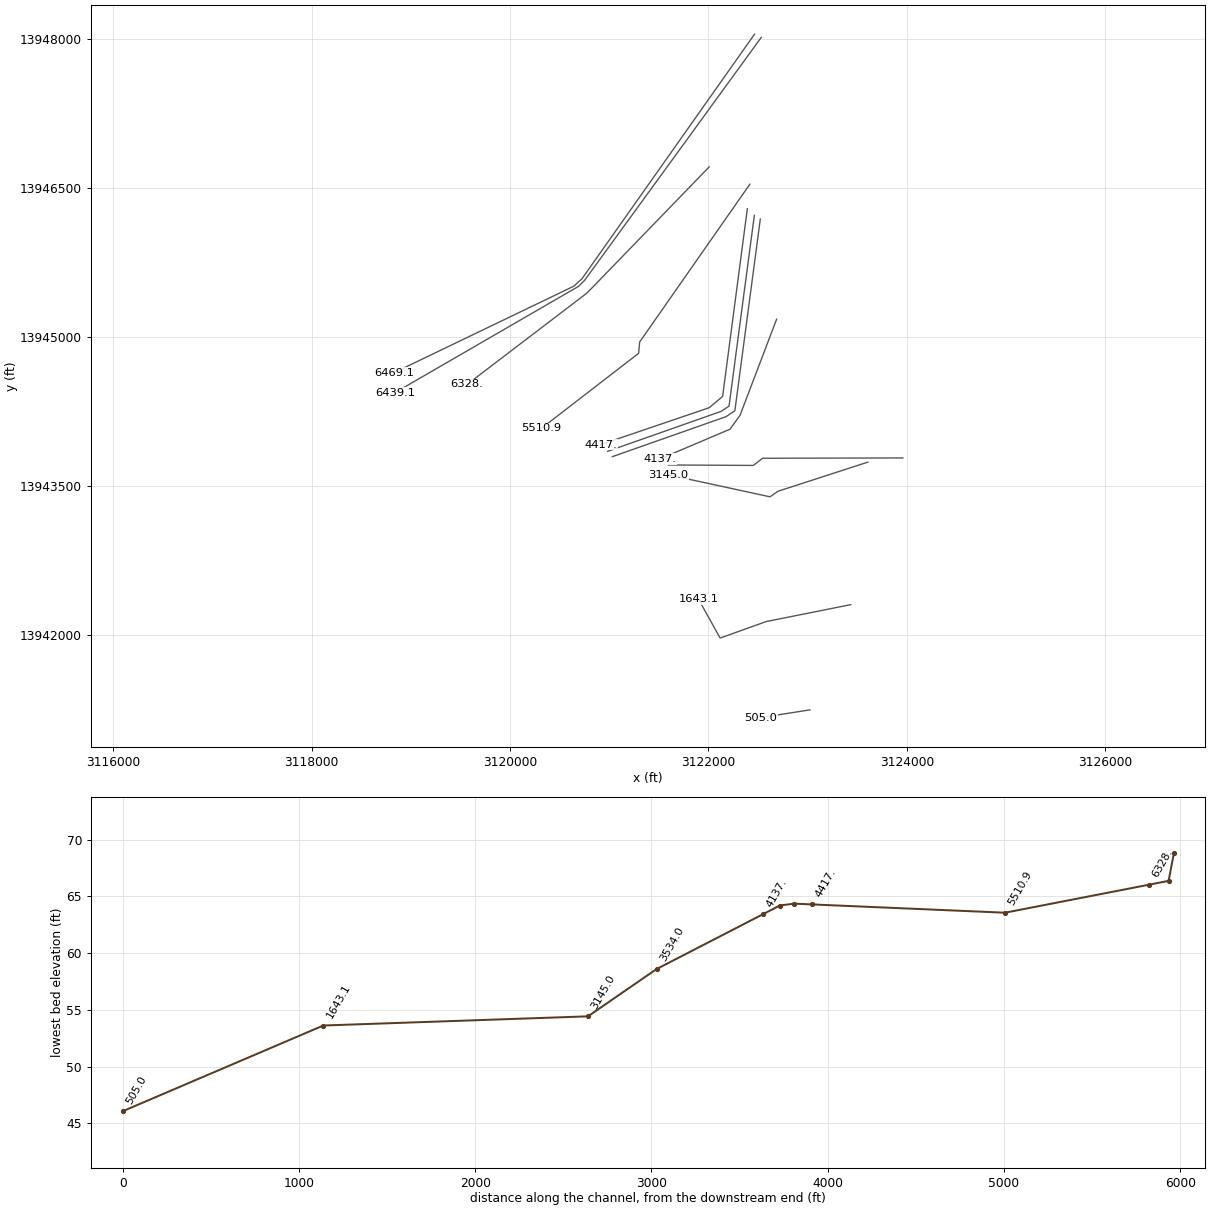
HEC-RAS study K112-00-00.prj: K112-00-00

--- K112-00-00.g01 (geometry) --- (continued)

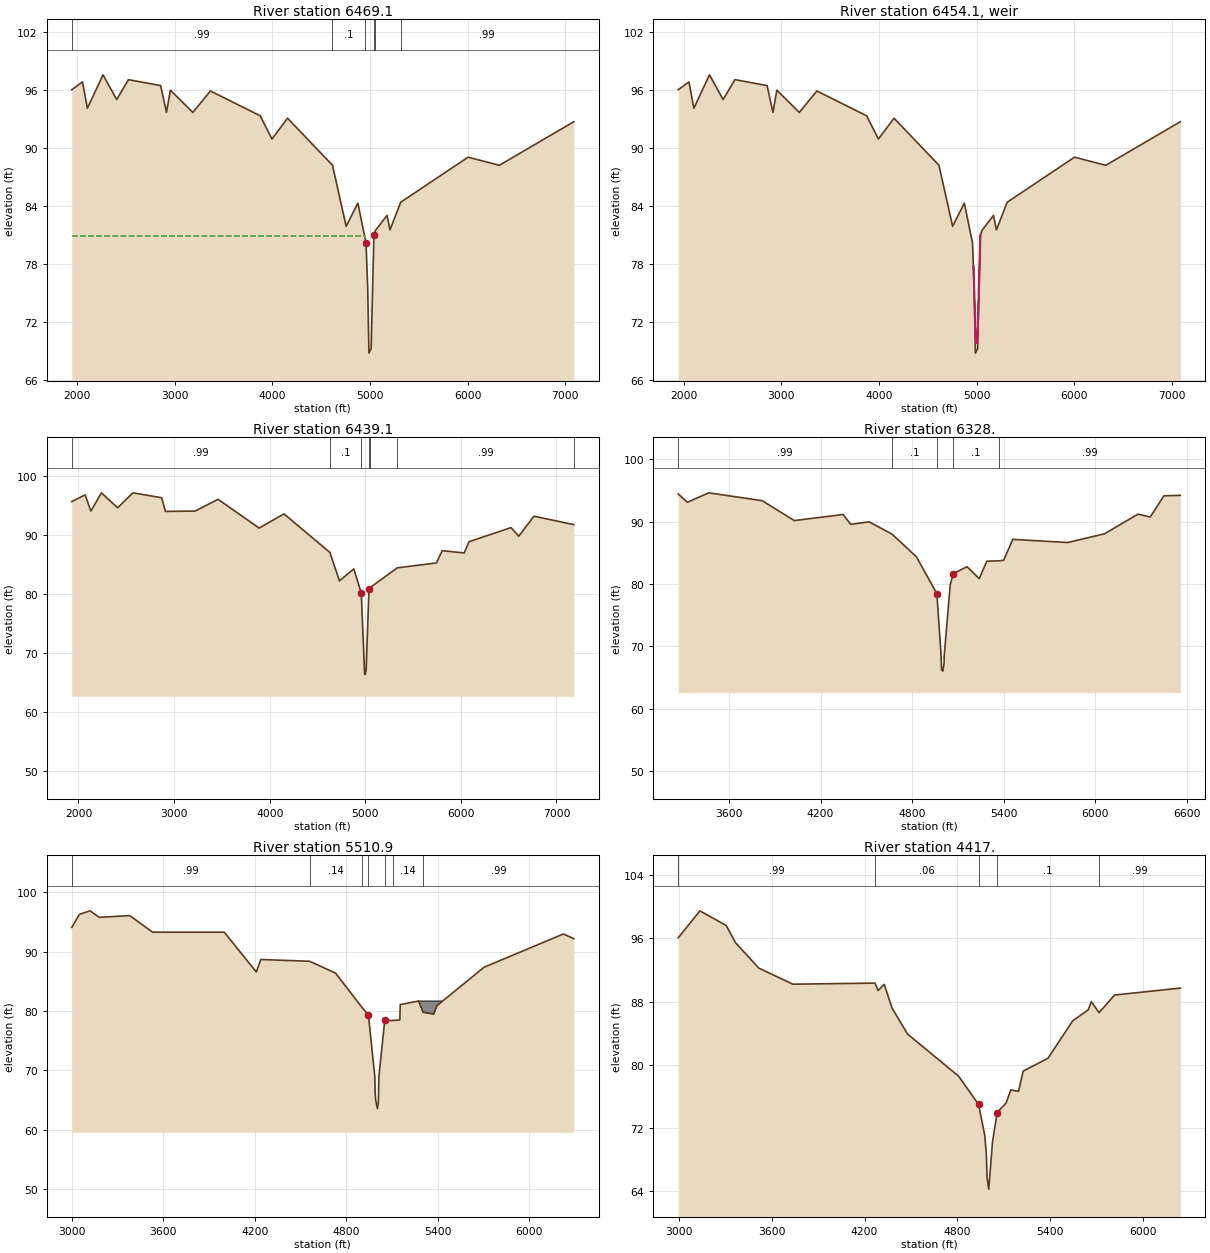
Type RM Length L Ch R = 1 ,6469.1  ,30,30,30
BEGIN DESCRIPTION:
Upstream Section of Bridge/Culvert/Weir
END DESCRIPTION:
XS GIS Cut Line= 5
      3122464.14      13948052.4       3120723.9     13945586.25
      3120663.12     13945531.61      3120641.78     13945512.34
      3118827.78     13944639.82
#Sta/Elev= 30
  1945.4   96.05  2055.4   96.86  2105.4   94.13  2265.4   97.59  2405.4   95.03
  2525.4   97.09  2855.4   96.48  2915.4   93.71  2955.4      96  3185.4    93.7
  3365.4   95.92  3875.4   93.35  3995.4   90.95  4155.4    93.1  4615.4   88.24
  4755.4   81.92  4875.4   84.32  4951.8   80.55  4958.9   80.23  4976.4   75.46
  4988.7    68.8  5011.4   69.27  5039.6   80.97  5055.6   81.49  5174.2   83.05
  5204.2   81.55  5314.2   84.41  6004.2   89.07  6324.2   88.23  7087.2   92.74
#Mann= 6 ,-1 , 0
  1945.4     .99       0  4615.4      .1       0  4951.8     .04       0
  5039.6    .045       0  5055.6      .1       0  5314.2     .99       0
#XS Ineff= 2 , 0
       0    4949   80.89  5049.6       0   80.89
Permanent Ineff=
       F       F
Bank Sta=4958.9,5039.6
XS Rating Curve= 0
Exp/Cntr=.7,.5

Type RM Length L Ch R = 5 ,6454.1  ,,,
BEGIN DESCRIPTION:
Structure ID: K112-00-00-S2  300FT DS REYNALDO DRIVE
END DESCRIPTION:
IW Pilot Flow=0
#Inline Weir SE= 17
 4967.8277.80101  4969.3   77.82  4976.4   75.45  4987.5   71.36  4988.5      71
  4988.7   70.93  4991.8   69.83  4999.4   69.83  5007.8   69.82  5011.4   71.08
  5011.5   71.11  5012.2   71.36  5023.8   75.42  5028.5   77.23  5037.9   80.39
    5039   80.76  5039.6   80.96
IW Dist,WD,Coef,Skew,MaxSub,Min_El,Is_Ogee,SpillHt,DesHd
9,1,3,0,.95,, 0 ,,,3,3,

Type RM Length L Ch R = 1 ,6439.1  ,105.1,111.1,113.1
BEGIN DESCRIPTION:
Cross Section FIELD_DS
Located At: 300FT DS REYNALDO DRIVE
END DESCRIPTION:
XS GIS Cut Line= 4
      3122531.93      13948020.2      3120751.49     13945571.63
       3120689.2     13945510.41      3118839.63     13944439.79
#Sta/Elev= 30
  1929.7   95.67  2069.7   96.82  2129.7   94.06  2239.7   97.16  2409.7   94.63
  2569.7   97.16  2869.7   96.33  2909.7   94.01  3219.7   94.07  3459.7   96.06
  3889.7   91.19  4149.7   93.59  4629.7   87.06  4729.7   82.24  4879.7   84.27
  4958.2   80.17  4993.1   66.43  5000.3   66.38  5008.9   67.13  5038.7   80.84
  5054.5   81.15  5334.5   84.45  5744.5   85.28  5804.5   87.36  6034.5   86.97
  6084.5   88.87  6524.5   91.27  6604.5    89.8  6764.5    93.2  7181.6   91.77
#Mann= 7 ,-1 , 0
  1929.7     .99       0  4629.7      .1       0  4958.2     .04       0
  5038.7    .045       0  5054.5      .1       0  5334.5     .99       0
  7181.6      .2       0
#Block Obstruct= 2 ,-1
    5273    5439    81.7    9000    9001      50
Bank Sta=4958.2,5038.7
XS Rating Curve= 0
Exp/Cntr=.7,.5

Type RM Length L Ch R = 1 ,6328.   ,772.9,817.1,831.8
BEGIN DESCRIPTION:
K112-00-00-S3_REYNALDO - US - XS 1
LIDAR overbanks - interpolated channel
END DESCRIPTION:
XS GIS Cut Line= 4
      3122006.81     13946714.75      3120828.41     13945497.91
      3120766.13     13945436.69      3119567.57     13944522.91
#Sta/Elev= 30
  3268.1   94.47  3328.1   93.14  3468.1   94.65  3818.1   93.39  4028.1    90.2
  4348.1   91.17  4398.1   89.59  4518.1      90  4668.1   88.03  4828.1   84.39
    4962   78.48 4988.08   69.15 4993.12   66.24 5000.66   66.04 5009.52   67.38
 5009.83    68.4  5049.3   79.83  5069.3   81.67  5159.3    82.8  5239.3   80.89
  5289.3   83.68  5369.3   83.74  5399.3   83.83  5459.3   87.18  5819.3   86.68
  6059.3   88.07  6279.3   91.23  6359.3   90.77  6449.3   94.17  6556.5   94.25
#Mann= 5 ,-1 , 0
  3268.1     .99       0  4668.1      .1       0    4962     .04       0
  5069.3      .1       0  5369.3     .99       0
#Block Obstruct= 2 ,-1
    5273    5439    81.7    9000    9001      50
Bank Sta=4962,5069.3
XS Rating Curve= 0
Exp/Cntr=.3,.1

Type RM Length L Ch R = 1 ,5510.9  ,1093.9,1093.9,1031
BEGIN DESCRIPTION:
Cross Section K112-00-00-X5; Block obstruction on right where ditches for road drainage located VRR
END DESCRIPTION:
XS GIS Cut Line= 4
      3122416.89     13946540.57      3121306.41     13944950.65
      3121295.83     13944836.39      3120315.42     13944079.81
#Sta/Elev= 30
  2999.1    94.1  3049.1    96.3  3119.1    96.9  3179.1    95.8  3379.1    96.1
  3529.1    93.3  3999.1    93.3  4209.1    86.6  4239.1    88.7  4559.1    88.4
  4729.1    86.4    4905   80.54  4944.8   79.32  4986.6   68.89  4988.8   66.17
  4992.1      65  5003.3   63.57  5009.6   64.64  5013.2   69.01  5051.4   78.42
  5104.2   78.42  5150.5   78.52  5153.2    81.1  5273.2    81.7  5303.2    79.8
  5373.2    79.5  5393.2    80.9  5703.2    87.4  6223.2      93  6291.6    92.2
#Mann= 7 ,-1 , 0
  2999.1     .99       0  4559.1     .14       0    4905    .045       0
  4944.8     .04       0  5051.4    .045       0  5104.2     .14       0
  5303.2     .99       0
#Block Obstruct= 2 ,-1
    5273    5439    81.7    9000    9001      50
Bank Sta=4944.8,5051.4
XS Rating Curve= 0
Exp/Cntr=.3,.1

Type RM Length L Ch R = 1 ,4417.   ,119,103.4,66
BEGIN DESCRIPTION:
K112-00-00-S1_TREASCHWIG DR - US - XS 4
LIDAR overbanks - interpolated channel
END DESCRIPTION:
XS GIS Cut Line= 4
      3122391.54     13946294.27      3122142.26     13944401.74
      3122005.71      13944287.7      3120912.81     13943916.02
#Sta/Elev= 30
  2997.3   96.09  3137.3    99.5  3307.3   97.64  3367.3   95.46  3517.3   92.26
  3737.3   90.22  4267.3   90.36  4287.3   89.42  4327.3    90.2  4377.3   87.21
  4477.3   83.92  4807.3   78.59  4936.2   75.01  4976.2   71.08 4986.18   68.77
 4990.81    65.8 5001.84    64.3  5026.2    70.3  5056.2   73.99  5114.1    75.2
  5144.1   76.85  5194.1   76.67  5224.1   79.23  5384.1   80.85  5544.1   85.59
  5644.1   86.98  5664.1      88  5714.1   86.62  5814.1   88.85  6238.5   89.73
#Mann= 5 ,-1 , 0
  2997.3     .99       0  4267.3     .06       0  4936.2     .04       0
  5056.2      .1       0  5714.1     .99       0
Bank Sta=4936.2,5056.2
XS Rating Curve= 0
Exp/Cntr=.5,.3

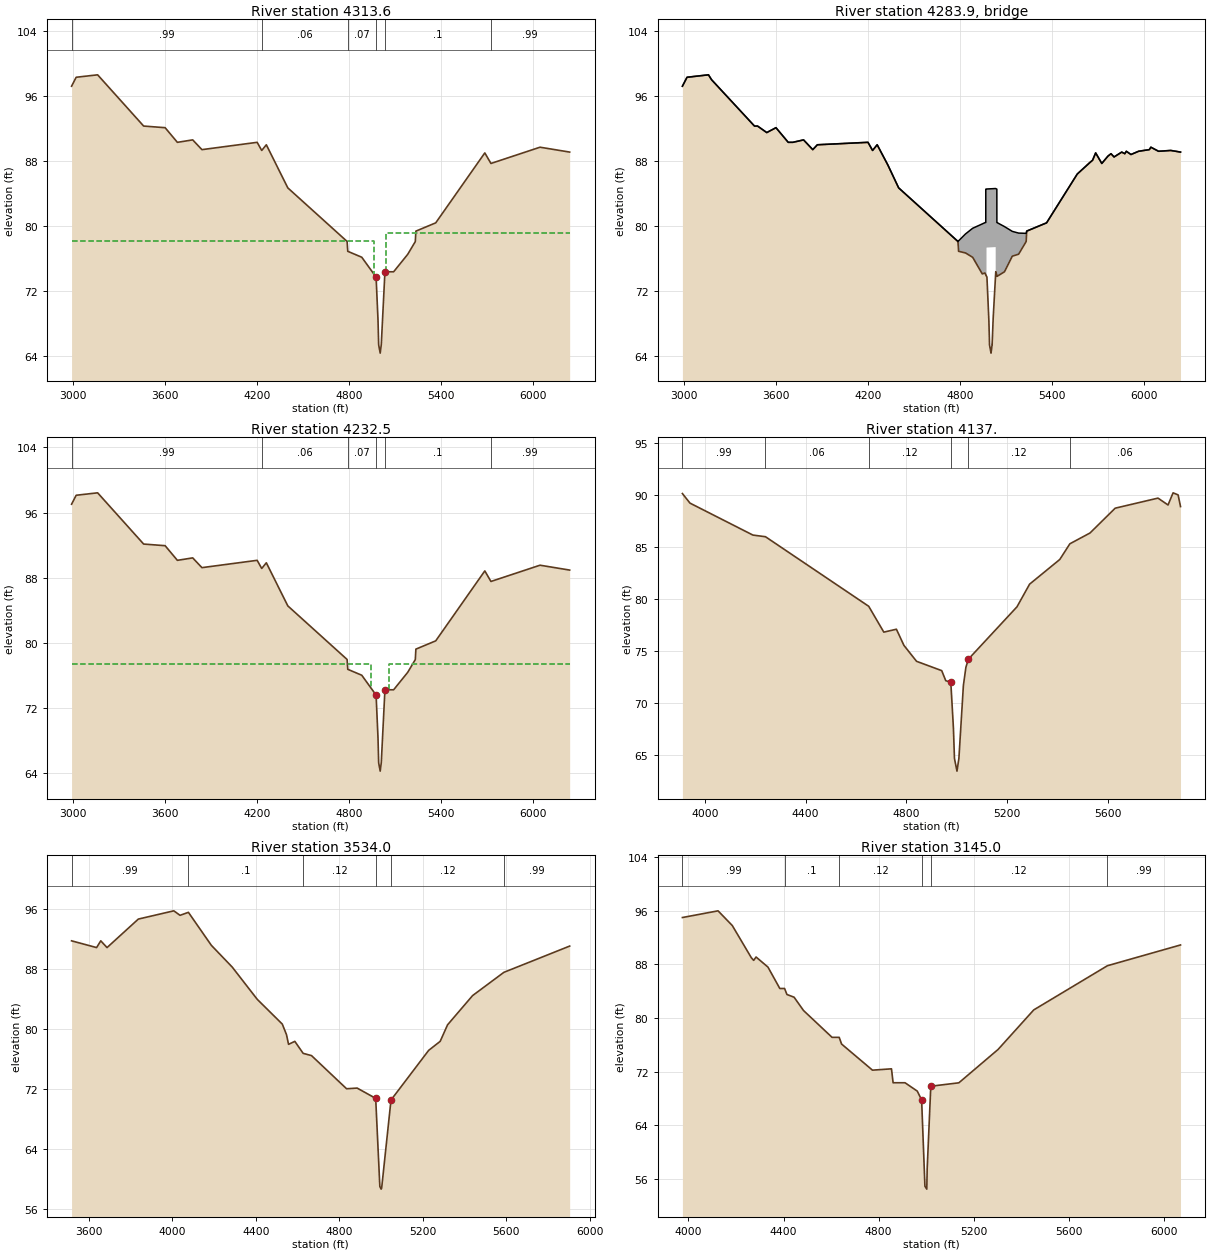
Type RM Length L Ch R = 1 ,4313.6  ,81.1,81.1,81.1
BEGIN DESCRIPTION:
Upstream Section of Bridge/Culvert/Weir
END DESCRIPTION:
XS GIS Cut Line= 4
      3122462.05     13946226.96      3122206.93     13944304.22
      3122127.77     13944251.44      3120983.32     13943848.71
#Sta/Elev= 30
  2989.2   97.19  3019.2   98.29  3159.2   98.59  3459.2   92.29  3599.2   92.09
  3679.2   90.29  3779.2   90.59  3839.2   89.39  4199.2   90.29  4229.2   89.29
  4259.2   89.99  4399.2   84.69  4785.9    78.1  4790.2   76.89  4881.6   76.16
    4975   73.72  4987.5   68.42  4991.7   65.39  5001.7   64.37 5008.81   65.42
  5032.6   74.38  5089.3   74.37  5181.6   76.53  5230.7   78.09  5234.4   79.37
  5363.9   80.39  5683.9   88.99  5723.9   87.69  6043.9   89.69  6237.2   89.09
#Mann= 6 ,-1 , 0
  2989.2     .99       0  4229.2     .06       0  4790.2     .07       0
    4975     .04       0  5032.6      .1       0  5723.9     .99       0
#XS Ineff= 2 , 0
       0    4962   78.11    5042       0   79.11
Permanent Ineff=
       F       F
Bank Sta=4975,5032.6
XS Rating Curve= 0
Exp/Cntr=.5,.3

Type RM Length L Ch R = 3 ,4283.9  ,,,
BEGIN DESCRIPTION:
TREASCHWIG DRIVE
Structure ID: K112-00-00-S1
END DESCRIPTION:
Bridge Culvert--1,0,-1,-1, 0
Deck Dist Width WeirC Skew NumUp NumDn MinLoCord MaxHiCord MaxSubmerge Is_Ogee
10,39.4,2.6,0, 57, 57, , , .95, 0, ,,,
  2989.2  3019.2  3159.2  3179.2  3459.2  3479.2  3539.2  3599.2  3679.2  3709.2
  3779.2  3839.2  3869.2  4199.2  4229.2  4259.2  4329.2  4399.2  4785.8  4790.2
  4834.8  4881.6  4944.6  4961.7 4967.29  4967.4    4972    4972 5031.99 5031.99
  5032.6  5039.6 5039.81    5041  5089.3  5140.3  5181.6  5230.7  5234.4  5363.9
  5563.9  5663.9  5683.9  5723.9  5763.9  5783.9  5803.9  5853.9  5873.9  5883.9
  5913.9  5963.9  6033.9  6043.9  6093.9  6173.9  6237.2
    97.2    98.3    98.6      98    92.3    92.3    91.5    92.1    90.3    90.3
    90.6    89.4      90    90.3    89.3      90    87.5    84.7   78.11   78.19
   79.03   79.73   80.27   80.42   80.44   84.54   84.56   84.56   84.62   84.62
   84.61   84.54   80.44   80.43   79.94   79.35   79.14   79.11   79.39    80.4
    86.4    88.1      89    87.7    88.6    88.9    88.5    89.1    88.9    89.2
    88.8    89.2    89.4    89.7    89.2    89.3    89.1
    97.2    98.3    98.6      98    92.3    92.3    91.5    92.1    90.3    90.3
    90.6    89.4      90    90.3    89.3      90    87.5    84.7   78.11    76.9
    76.7   76.17   74.12   74.23   74.02   74.02   73.85   77.36   77.42   74.22
   74.39   73.92    73.9   73.82   74.38    76.3   76.54    78.1   79.38    80.4
    86.4    88.1      89    87.7    88.6    88.9    88.5    89.1    88.9    89.2
    88.8    89.2    89.4    89.7    89.2    89.3    89.1
  2989.2  3019.2  3159.2  3179.2  3459.2  3479.2  3539.2  3599.2  3679.2  3709.2
  3779.2  3839.2  3869.2  4199.2  4229.2  4259.2  4329.2  4399.2  4785.8  4790.2
  4834.8  4881.6  4944.6  4961.7 4967.29  4967.4    4972    4972 5031.99 5031.99
  5032.6  5039.6 5039.81    5041  5089.3  5140.3  5181.6  5230.7  5234.4  5363.9
  5563.9  5663.9  5683.9  5723.9  5763.9  5783.9  5803.9  5853.9  5873.9  5883.9
  5913.9  5963.9  6033.9  6043.9  6093.9  6173.9  6237.2
    97.2    98.3    98.6      98    92.3    92.3    91.5    92.1    90.3    90.3
    90.6    89.4      90    90.3    89.3      90    87.5    84.7   78.11   78.19
   79.03   79.73   80.27   80.42   80.44   84.54   84.56   84.56   84.62   84.62
   84.61   84.54   80.44   80.43   79.94   79.35   79.14   79.11   79.39    80.4
    86.4    88.1      89    87.7    88.6    88.9    88.5    89.1    88.9    89.2
    88.8    89.2    89.4    89.7    89.2    89.3    89.1
    97.1    98.2    98.5    97.9    92.2    92.2    91.4      92    90.2    90.2
    90.5    89.3    89.9    90.2    89.2    89.9    87.4    84.6   78.01    76.8
    76.6   76.07   74.02   74.13   73.92   73.92   73.75   77.26   77.32   74.12
   74.29   73.82    73.8   73.72   74.28    76.2   76.44      78   79.28    80.3
    86.3      88    88.9    87.6    88.5    88.8    88.4      89    88.8    89.1
    88.7    89.1    89.3    89.6    89.1    89.2      89
BR Coef= 1 , 0 , 0 ,1.25, 0 ,,,.8,-1,2,0,
WSPro=,,,, 1 ,,,, 0 ,,,, 0 ,,,,-1 ,-1 ,-1 , 0 , 0 , 0 , 0 , 0
BR U #Sta/Elev= 84
  2989.2    97.2  3019.2    98.3  3159.2    98.6  3179.2      98  3459.2    92.3
  3479.2    92.3  3489.8   92.16  3539.2    91.5  3599.2    92.1  3679.2    90.3
  3709.2    90.3  3779.2    90.6  3839.2    89.4  3869.2      90  4199.2    90.3
  4229.2    89.3  4259.2      90  4329.2    87.5  4399.2    84.7  4785.8   78.11
  4785.9   78.11  4790.2    76.9  4832.3   76.71  4834.8    76.7  4880.4   76.18
  4881.6   76.17  4944.6   74.12  4961.7   74.23  4963.4   74.17 4967.29   74.02
  4967.4   74.02 4967.51   74.01  4971.7   73.85 4971.81   73.85 4971.93   73.85
    4972   73.84    4975   73.73  4987.5   68.43  4991.1   66.01  4991.7    65.4
  5001.5    64.4  5001.7   64.38  5008.7   65.43 5008.81   65.43  5015.6   68.66
  5025.3   71.97 5031.87   74.15 5031.99   74.19  5032.1   74.22  5032.2   74.26
  5032.6   74.39 5039.49   73.92  5039.6   73.92 5039.81    73.9    5041   73.82
  5089.3   74.38  5092.3   74.49  5139.7   76.28  5140.3    76.3  5179.6   76.53
  5181.6   76.54  5230.7    78.1  5234.4   79.38  5243.5   79.45  5363.9    80.4
  5563.9    86.4  5643.9    87.8  5663.9    88.1  5683.9      89  5723.9    87.7
  5763.9    88.6  5783.9    88.9  5803.9    88.5  5853.9    89.1  5873.9    88.9
  5883.9    89.2  5913.9    88.8  5963.9    89.2  5990.5   89.28  6033.9    89.4
  6043.9    89.7  6093.9    89.2  6173.9    89.3  6237.2    89.1
BR U #Mann= 6
  2989.2     .99  4229.2     .06  4790.2     .07    4975     .04  5032.6      .1
  5723.9     .99
BR U Banks=4975,5032.6
BR D #Sta/Elev= 84
  2989.2    97.1  3019.2    98.2  3159.2    98.5  3179.2    97.9  3459.2    92.2
  3479.2    92.2  3489.8   92.06  3539.2    91.4  3599.2      92  3679.2    90.2
  3709.2    90.2  3779.2    90.5  3839.2    89.3  3869.2    89.9  4199.2    90.2
  4229.2    89.2  4259.2    89.9  4329.2    87.4  4399.2    84.6  4785.8   78.01
  4785.9   78.01  4790.2    76.8  4832.3   76.61  4834.8    76.6  4880.4   76.08
  4881.6   76.07  4944.6   74.02  4961.7   74.13  4963.4   74.07 4967.29   73.92
  4967.4   73.92 4967.51   73.91  4971.7   73.75 4971.81   73.75 4971.93   73.75
    4972   73.74    4975   73.63  4987.5   68.33  4991.1   65.91  4991.7    65.3
  5001.5    64.3  5001.7   64.28  5008.7   65.33 5008.81   65.33  5015.6   68.56
  5025.3   71.87 5031.87   74.05 5031.99   74.09  5032.1   74.12  5032.2   74.16
  5032.6   74.29 5039.49   73.82  5039.6   73.82 5039.81    73.8    5041   73.72
  5089.3   74.28  5092.3   74.39  5139.7   76.18  5140.3    76.2  5179.6   76.43
  5181.6   76.44  5230.7      78  5234.4   79.28  5243.5   79.35  5363.9    80.3
  5563.9    86.3  5643.9    87.7  5663.9      88  5683.9    88.9  5723.9    87.6
  5763.9    88.5  5783.9    88.8  5803.9    88.4  5853.9      89  5873.9    88.8
  5883.9    89.1  5913.9    88.7  5963.9    89.1  5990.5   89.18  6033.9    89.3
  6043.9    89.6  6093.9    89.1  6173.9    89.2  6237.2      89
BR D #Mann= 6
  2989.2     .99  4229.2     .06  4790.2     .07    4975     .04  5032.6      .1
  5723.9     .99
BR D Banks=4975,5032.6
BC Design=,, 0 ,, 0 ,,,,,,
BC HTab HWMax=98.59

Type RM Length L Ch R = 1 ,4232.5  ,64,95.5,142
BEGIN DESCRIPTION:
Downstream Section of Bridge/Culvert/Weir
END DESCRIPTION:
XS GIS Cut Line= 4
      3122522.12      13946189.2       3122265.8      13944257.4
      3122177.01      13944198.2      3121030.19      13943794.7
#Sta/Elev= 30
  2989.2   97.02  3019.2   98.12  3159.2   98.42  3459.2   92.12  3599.2   91.92
  3679.2   90.12  3779.2   90.42  3839.2   89.22  4199.2   90.12  4229.2   89.12
  4259.2   89.82  4399.2   84.52  4785.9   77.93  4790.2   76.72  4881.6   75.99
    4975   73.55  4987.5   68.25  4991.7   65.22  5001.7    64.2 5008.81   65.25
  5032.6   74.21  5089.3    74.2  5181.6   76.36  5230.7   77.92  5234.4    79.2
  5363.9   80.22  5683.9   88.82  5723.9   87.52  6043.9   89.52  6237.2   88.92
#Mann= 6 ,-1 , 0
  2989.2     .99       0  4229.2     .06       0  4790.2     .07       0
    4975     .04       0  5032.6      .1       0  5723.9     .99       0
#XS Ineff= 2 , 0
       0    4942   77.34    5062       0   77.34
Permanent Ineff=
       F       F
Bank Sta=4975,5032.6
XS Rating Curve= 0
Exp/Cntr=.5,.3

Type RM Length L Ch R = 1 ,4137.   ,643,603,426
BEGIN DESCRIPTION:
K112-00-00-S1_TREASCHWIG DR - DS - XS 1
LIDAR overbanks - interpolated channel
END DESCRIPTION:
XS GIS Cut Line= 4
      3122686.39     13945180.04      3122317.85     13944211.73
      3122216.54     13944071.61      3121508.15     13943771.07
#Sta/Elev= 30
    3911   90.17    3941   89.25    4191   86.17    4241   86.01    4651   79.31
    4711   76.82    4761    77.1    4791   75.54    4841   74.01    4941   73.11
  4957.1   72.14  4977.1      72 4987.45   67.59 4991.64   64.64 5001.62   63.43
 5009.24   64.66  5027.1   71.69  5037.1   73.44  5047.1   74.22    5240   79.26
    5290   81.44    5410   83.82    5450   85.33    5530   86.37    5630   88.76
    5800   89.73    5840   89.07    5860   90.24    5880   90.04  5889.5   88.92
#Mann= 6 ,-1 , 0
    3911     .99       0    4241     .06       0    4651     .12       0
  4977.1     .04       0  5047.1     .12       0    5450     .06       0
Bank Sta=4977.1,5047.1
XS Rating Curve= 0
Exp/Cntr=.3,.1

Type RM Length L Ch R = 1 ,3534.0  ,357,389,314
BEGIN DESCRIPTION:
Cross Section K112-00-00-X04
END DESCRIPTION:
XS GIS Cut Line= 4
      3123958.85     13943782.01      3122544.41     13943778.87
      3122451.66     13943706.63      3121596.39     13943711.28
#Sta/Elev= 30
  3517.3    91.7  3637.3    90.8  3657.3    91.7  3687.3    90.8  3837.3    94.6
  4007.3    95.7  4037.3    95.1  4077.3    95.5  4187.3    91.1  4287.3    88.2
  4407.3    83.9  4527.3    80.6  4547.3    79.2  4557.3    77.9  4587.3    78.3
  4627.3    76.7  4667.3    76.4  4835.4   71.98    4886   72.07  4974.9    70.7
  4994.8   58.96  5001.1    58.6  5003.4   58.72  5048.3   70.48  5228.9    77.1
    5284    78.3  5319.3    80.5  5439.3    84.4  5589.3    87.5  5904.6      91
#Mann= 6 ,-1 , 0
  3517.3     .99       0  4077.3      .1       0  4627.3     .12       0
  4974.9     .07       0  5048.3     .12       0  5589.3     .99       0
Bank Sta=4974.9,5048.3
XS Rating Curve= 0
Exp/Cntr=.3,.1

Type RM Length L Ch R = 1 ,3145.0  ,1470,1501.9,1400
BEGIN DESCRIPTION:
Cross Section K112-00-00-X3
END DESCRIPTION:
XS GIS Cut Line= 4
      3123605.19     13943739.57       3122700.1     13943446.33
      3122620.29     13943390.27      3121596.39     13943612.26
#Sta/Elev= 30
  3974.5      95  4124.5      96  4184.5    93.8  4264.5      89  4274.5    88.6
  4284.5    89.1  4334.5    87.6  4384.5    84.4  4404.5    84.4  4414.5    83.5
  4444.5    83.1  4484.5    81.1  4604.5    77.1  4634.5    77.1  4644.5    76.1
  4774.5    72.2  4854.5    72.4  4861.4   70.32  4911.5   70.32  4963.1   69.07
  4981.4   67.75  4995.3   54.86  5003.1   54.43  5004.8   57.48    5020    69.8
  5138.1   70.31  5303.4    75.3  5453.4    81.2  5763.4    87.8  6071.1    90.9
#Mann= 6 ,-1 , 0
  3974.5     .99       0  4404.5      .1       0  4634.5     .12       0
  4981.4     .07       0    5020     .12       0  5763.4     .99       0
Bank Sta=4981.4,5020
XS Rating Curve= 0
Exp/Cntr=.3,.1

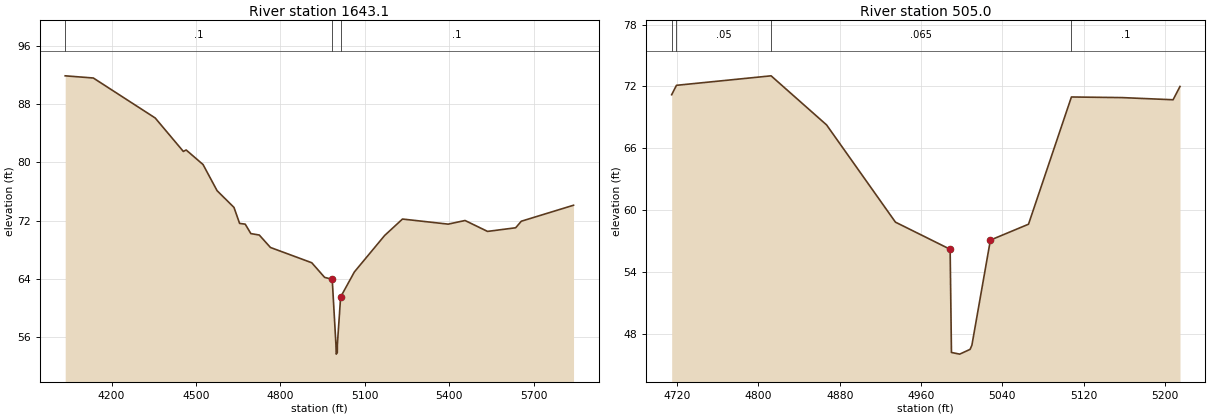
Type RM Length L Ch R = 1 ,1643.1  ,1063,1138.1,1116
BEGIN DESCRIPTION:
Cross Section K112-00-00-X02
END DESCRIPTION:
XS GIS Cut Line= 4
      3123433.45      13942303.5      3122581.63     13942133.35
      3122117.63     13941967.11      3121900.23     13942356.14
#Sta/Elev= 30
    4035    91.9    4135    91.6    4355    86.1    4455    81.5    4465    81.7
    4525    79.7    4575    76.1    4635    73.8    4655    71.6    4675    71.5
    4695    70.2    4725      70  4764.7   68.29  4911.5   66.19  4957.2   64.18
  4984.3   63.91  4997.4      55  4998.6   53.62  5002.4   53.83  5002.6   54.95
  5014.2   61.48    5063   64.92  5170.7   69.94  5234.1    72.2  5396.5    71.5
  5456.5      72  5536.5    70.5  5636.5      71  5656.5    71.9  5842.2    74.1
#Mann= 3 ,-1 , 0
    4035      .1       0  4984.3    .055       0  5014.2      .1       0
Bank Sta=4984.3,5014.2
XS Rating Curve= 0
Exp/Cntr=.3,.1

Type RM Length L Ch R = 1 ,505.0   ,0,0,0
BEGIN DESCRIPTION:
Cross Section K112-00-00-X1
END DESCRIPTION:
XS GIS Cut Line= 2
      3123022.61      13941243.4      3122528.59     13941166.21
#Sta/Elev= 16
  4714.7    71.2  4719.4   72.11  4812.5   73.03  4867.1   68.27  4934.8   58.85
  4988.6   56.22  4989.9   46.22    4998   46.06  5008.2   46.52    5010   46.92
  5028.2   57.11  5065.7   58.65  5107.9   70.98  5157.8   70.92  5207.9   70.71
  5214.7      72
#Mann= 4 ,-1 , 0
  4714.7     .99       0  4719.4     .05       0  4812.5    .065       0
  5107.9      .1       0
Bank Sta=4988.6,5028.2
XS Rating Curve= 0
Exp/Cntr=.3,.1

Chan Stop Cuts=-1